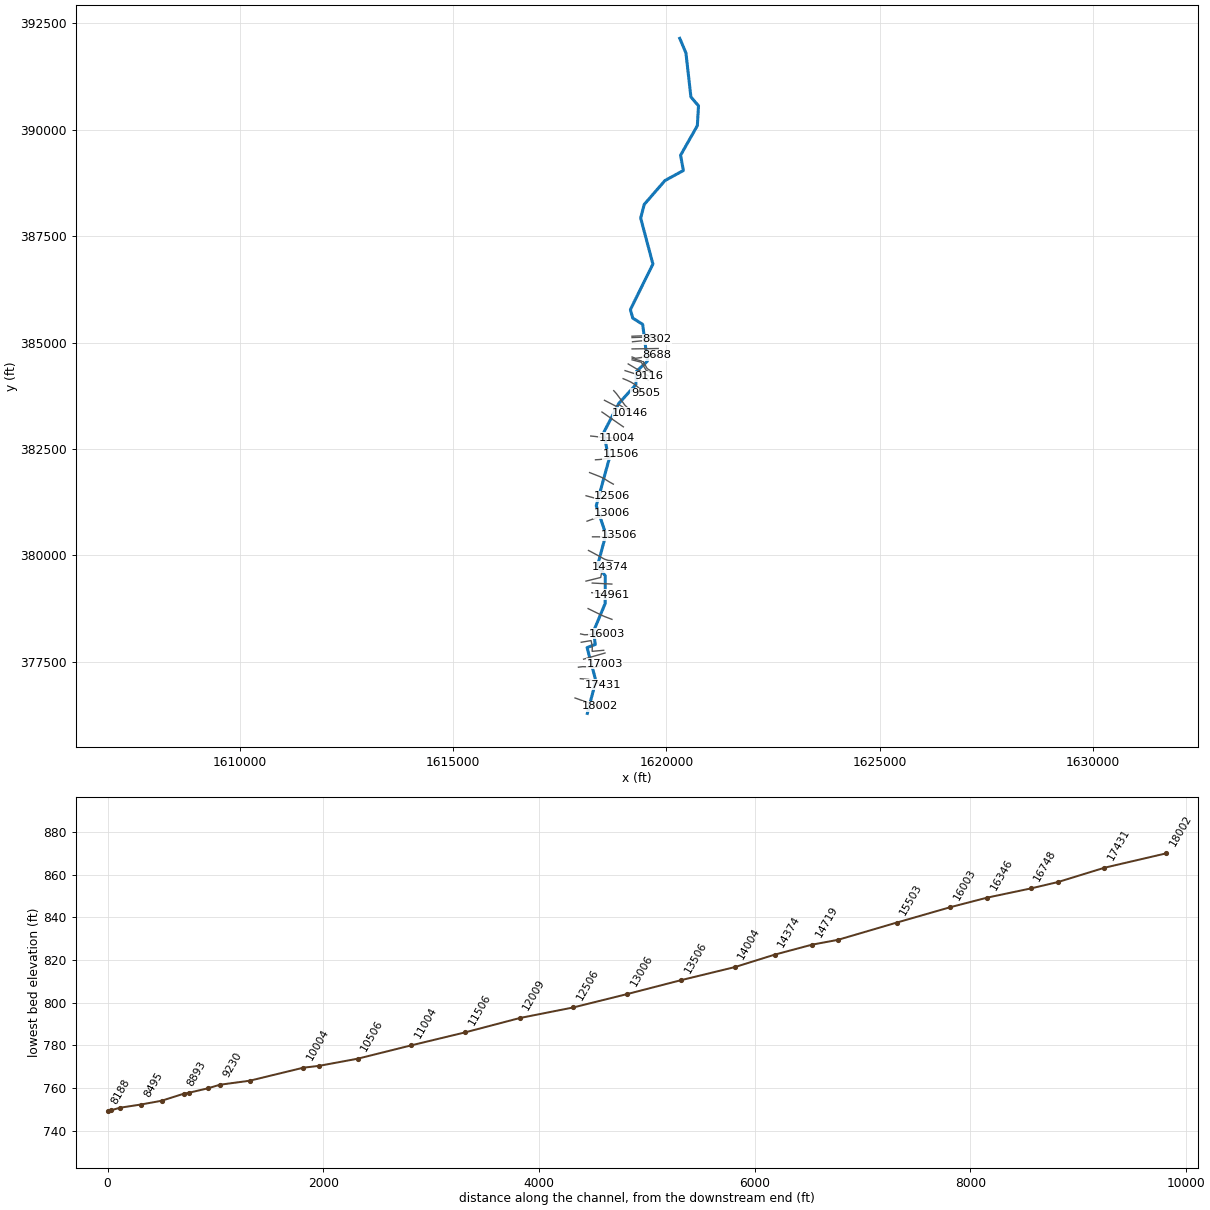
--- BRUSHRN.prj (project) ---

Proj Title=BRUSHRN
Current Plan=p01
Default Exp/Contr=0,0
English Units
Geom File=g01
Flow File=f01
Plan File=p01
BEGIN DESCRIPTION:
---------- MODELED AS PART OF WVEMD CTP PROGRAM, 2023----------
Stream Name: Brush Run
Flood Zone:  AFH
Wetzel County, WV
HEC-RAS Version: RAS 6.3
Vertical Datum: NAVD88
Projection: NAD 1983 StatePlane West Virginia S FIPS 4702 (US Feet)
Terrain: 1-meter West Virginia FEMA R3 South Central (collected 2018-2020)
Land Use: 2019 NLCD
Hydrologic Method:
WV SIR2010-5033 regression equations
Additional Model Notes:
None
END DESCRIPTION:
DSS Export Rating Curves= 0
DSS Export Rating Curve Sorted= 0
DSS Export Volume Flow Curves= 0
DXF OffsetX= 0
DXF OffsetY= 0
DXF ScaleX= 0
DXF ScaleY= 0

--- BRUSHRN.p01 (plan) ---

Plan Title=Floodplain
Program Version=6.30
Short Identifier=Floodplain
Geom File=g01
Flow File=f01
Subcritical Flow
K Sum by GR= 0
Std Step Tol= 0.01
Critical Tol= 0.01
Num of Std Step Trials= 20
Max Error Tol= 0.3
Flow Tol Ratio= 0.001
Split Flow NTrial= 30
Split Flow Tol= 0.02
Split Flow Ratio= 0.02
Log Output Level= 0
Friction Slope Method= 1
Unsteady Friction Slope Method= 2
Unsteady Bridges Friction Slope Method= 1
Parabolic Critical Depth
Global Vel Dist= 0 , 0 , 0
Global Log Level= 0
CheckData=True
Encroach Param=-1 ,0,0, 0
Mapping Interval=1HOUR
Computation Time Step Use Courant=        0
Computation Time Step Use Time Series=    0
Computation Time Step Count To Double=0
Computation Time Step Max Doubling=0
Computation Time Step Max Halving=0
Computation Time Step Residence Courant=0
Run HTab= 0
Run UNet= 0
Run Sediment= 0
Run PostProcess= 0
Run WQNet= 0
Run RASMapper= 0
UNET Theta= 0
UNET Theta Warmup= 0
UNET ZTol= 0
UNET ZSATol= 0
UNET MxIter= 0
UNET Max Iter WO Improvement= 0
UNET MaxInSteps= 0
UNET DtIC= 0
UNET DtMin= 0
UNET MaxCRTS= 0
UNET WFStab= 0
UNET SFStab= 0
UNET WFX= 1
UNET SFX= 1
UNET Gravity=32.17405
UNET 1D Methodology=Finite Difference
UNET DSS MLevel= 1
UNET Pardiso=0
UNET DZMax Abort= 0
UNET Use Existing IB Tables= 0
UNET Froude Reduction=False
UNET Froude Limit= 0
UNET Froude Power= 0
UNET D1 Cores= 0
UNET WindReference=Eulerian
UNET WindDragFormulation=Hsu (1988)
UNET D2 Coriolis=0
UNET D2 Cores= 0
UNET D2 Theta= 1
UNET D2 Theta Warmup= 1
UNET D2 Z Tol= 0.01
UNET D2 Volume Tol= 0.01
UNET D2 Max Iterations= 20
UNET D2 Equation= 0
UNET D2 RampUpFraction=0.1
UNET D2 TimeSlices= 1
UNET D2 Turbulence Formulation=Non-Conservative (original)
UNET D2 Eddy Viscosity=0.3
UNET D2 Transverse Eddy Viscosity=0.1
UNET D2 Smagorinsky Mixing=0
UNET D2 BCVolumeCheck=0
UNET D2 Cores=0
UNET D2 SolverType=PARDISO (Direct)
UNET D2 Minimum Iterations= 3
UNET D2 Maximum Iterations= 30
UNET D2 Restart Number= 10
UNET D2 Relaxation Coeff=1.3
UNET D2 SOR Precondition Iterations= 10
UNET D2 ILUT Maximum Fill= 8
UNET D2 ILUT Tolerance=1E-08
UNET D2 Convergence Tolerance=0.00001
UNET D1D2 MaxIter= 0
UNET D1D2 ZTol=0.01
UNET D1D2 QTol=0.1
UNET D1D2 MinQTol=1
Write IC File= 0
Write IC File at Fixed DateTime=0
Write IC File at Sim End=0
Echo Input=False
Echo Parameters=False
Echo Output=False
Write Detailed= 0
HDF Write Warmup=0
HDF Write Time Slices=0
HDF Flush=0
HDF Compression= 1
HDF Chunk Size= 1
HDF Spatial Parts= 1
HDF Use Max Rows=0
HDF Fixed Rows= 1
Calibration Method= 0
Calibration Iterations= 20
Calibration Max Change=0.05
Calibration Tolerance=0.2
Calibration Maximum=1.5
Calibration Minimum=0.5
Calibration Optimization Method= 1
WQ AD Non Conservative
WQ ULTIMATE=-1
WQ Max Comp Step=1HOUR
WQ Output Interval=15MIN
WQ Output Selected Increments= 0
WQ Output face flow=0
WQ Output face velocity=0
WQ Output face area=0
WQ Output face dispersion=0
WQ Output cell volume=0
WQ Output cell surface area=0
WQ Output cell continuity=0
WQ Output cumulative cell continuity=0
WQ Output face conc=0
WQ Output face dconc_dx=0
WQ Output face courant=0
WQ Output face peclet=0
WQ Output face adv mass=0
WQ Output face disp mass=0
WQ Output cell mass=0
WQ Output cell source sink temp=0
WQ Output nsm pathways=0
WQ Output nsm derived pathways=0
WQ Create Restart=0
WQ Fixed Restart=0
WQ System Summary=0
WQ Write To DSS=0
Sorting and Armoring Iterations= 10
XS Update Threshold= 0.02
Bed Roughness Predictor= 0
Hydraulics Update Threshold= 0.02
Energy Slope Method= 1
Volume Change Method= 1
Sediment Retention Method= 0
Sediment TS Multiplier= 1
Warm Up Method= 0
XS Weighting Method= 0
Number of US Weighted Cross Sections= 1
Number of DS Weighted Cross Sections= 1
Upstream XS Weight=0
Main XS Weight=1
Downstream XS Weight=0
Number of DS XS's Weighted with US Boundary= 1
Upstream Boundary Weight= 1
Weight of XSs Associated with US Boundary= 0
Number of US XS's Weighted with DS Boundary= 1
Downstream Boundary Weight= 0.5
Weight of XSs Associated with DS Boundary= 0.5
Percentile Method= 0
Sediment Output Level= 3
Mass or Volume Output= 0
Output Increment Type= 1
Profile and TS Output Increment= 1
Transport Output Increment 1
XS Output Flag= 0
XS Output Increment= 10
Read HDF5 Sediment Hotstart= 0
Sediment Hotstart Type= 0
Write Gradation File= 0
Read Gradation Hotstart= 0
Write HDF5 File= 1
Write Binary Output= 1
Write DSS Sediment File= 0
DSS Sediment Output Type= 1
SV Curve= 0
Specific Gage Flag= 0
Subcell Erosion Methods= 0
Subcell Deposition Methods= 0
Advection Scheme= 1
Matrix Solver= 0
Implicit Weighting Factor= 1
Maximum Outer Loop Convergence Iterations= 5
Convergence Maximum Absolute= 0.001
Convergence RMSE= 0.0001
Grain Fractions Max Abs Error= 0.001
Max Subgrid Regions= 1
Max Subgrid Length Scale= 3.402823E+38
Initial Layer Thickness= 3.402823E+38
Min Layer Thickness= 3.402823E+38
Max Layer Thickness= 3.402823E+38
Number of Layers= 5

--- BRUSHRN.f01 (steady flow) ---

Flow Title=Flow
Program Version=6.31
Number of Profiles= 1
Profile Names=F01pct
River Rch & RM=BRUSHRN,Main,18002
     589
River Rch & RM=BRUSHRN,Main,17003
     656
River Rch & RM=BRUSHRN,Main,15503
     753
River Rch & RM=BRUSHRN,Main,14374
     837
River Rch & RM=BRUSHRN,Main,12506
     932
River Rch & RM=BRUSHRN,Main,10506
    1080
River Rch & RM=BRUSHRN,Main,7688
    1220
River Rch & RM=BRUSHRN,Main,4633
    1390
Boundary for River Rch & Prof#=BRUSHRN,Main            , 1
Up Type= 0
Dn Type= 3
Dn Slope=0.00759
DSS Import GetInterval= 0
DSS Import GetPeak= 0
DSS Import FillOption= 0

--- BRUSHRN.g01 (geometry) ---

Geom Title=Geometry
Program Version=6.31

River Reach=BRUSHRN         ,Main
Reach XY= 30
     1618144.074      376285.325     1618344.346      377049.954
     1618138.733      377831.653     1618330.009      377903.299
     1618291.557      378219.133     1618563.352      378868.878
     1618565.652      379515.665     1618384.236      379762.482
     1618580.442      380491.103     1618353.343       381164.84
     1618650.444      382241.832     1618528.186      382884.017
1618881.73805421383568.240655125     1619283.428      384011.293
     1619294.931      384319.897     1619553.908      384562.771
     1619441.838      385427.783     1619209.481      385573.704
     1619154.267      385773.524      1619682.74      386844.272
     1619395.498      387925.208     1619479.304      388245.315
     1619964.723      388805.338     1620397.558      389042.953
      1620331.17      389400.526     1620725.018      390094.865
     1620752.173       390562.31     1620574.043      390770.019
1620456.99886152391806.072907679     1620311.974      392148.116

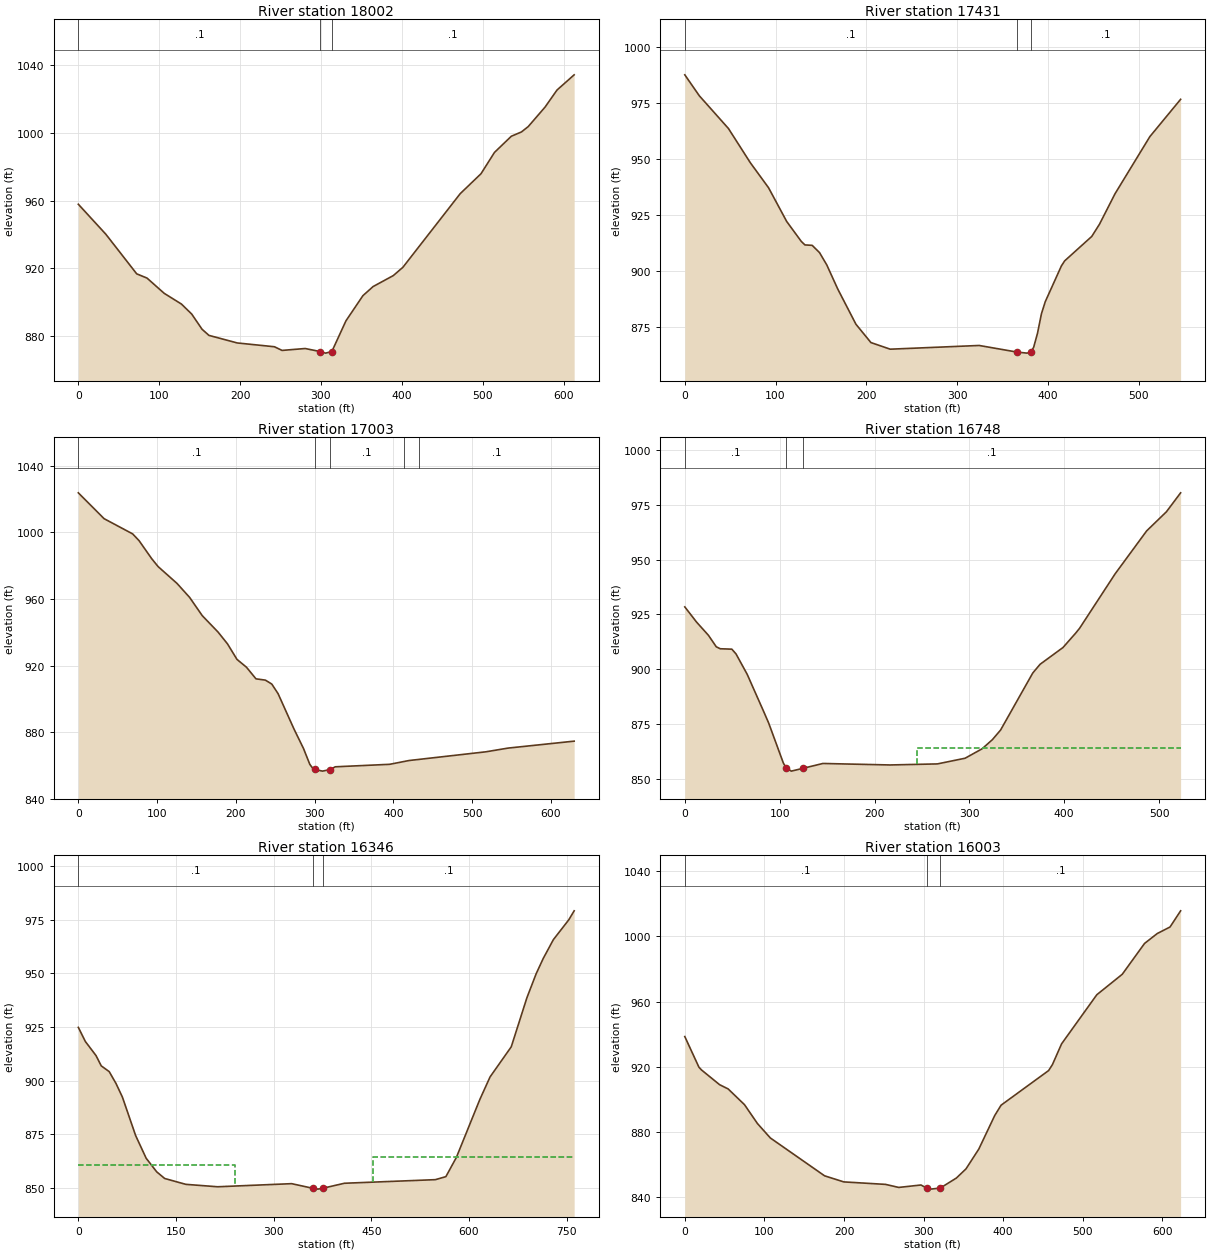
Type RM Length L Ch R = 1 ,18002   ,570.3,571.3,569.2
XS GIS Cut Line= 6
1617856.07091442376647.0649174151617944.63471368376615.712946013
1618027.01512635376585.6598564981618097.56813484376559.740288928
1618192.79038534 376529.094680921618438.62749209376456.788723171
#Sta/Elev= 30
       0  957.84      34  940.16    72.2  916.78    84.9   914.3   106.2  905.29
   127.5  898.97   140.2  893.07     153   884.1   161.5   880.5   196.5  876.03
   242.5  873.79   251.9  871.63   280.5  872.75   299.2  870.94   305.7  870.03
  313.46870.9515   330.9  889.06   351.9  903.92   364.5  909.29   389.5  915.77
   401.3  920.63   472.2  964.07   497.9  975.82   514.6  988.41   535.4  997.94
   547.9 1000.47   556.3 1003.63   577.1 1015.12   591.9 1025.19   613.1 1034.16
#Mann= 3 ,-1,0
       0      .1       0   299.2    .045       0  313.46      .1       0
Bank Sta=299.2,313.46
XS Rating Curve= 0 ,0
Exp/Cntr(USF)=0,0
Exp/Cntr=0.3,0.1

Type RM Length L Ch R = 1 ,17431   ,428.3,427.9,429.6
XS GIS Cut Line= 3
1617980.14739722377100.6932418311618177.20388272377084.628854427
1618503.84642662 376962.53951015
#Sta/Elev= 30
       0  987.64      16  978.28    48.1  963.66    72.2  948.38    92.3  937.19
   112.3  922.12   128.4   913.2   132.4  911.65   140.4  911.45   148.5   908.2
   156.5  902.69   168.5  891.99   188.6  876.21   205.1  868.02   226.4  865.06
   324.4  866.72   366.2  863.76   377.2   863.3  381.02863.7269   384.4  865.85
   388.7   872.2     393  880.85   397.2  886.25     415  902.25   418.6  904.51
   448.5  915.45     457   920.9   474.1   934.5   512.5  960.03   546.4   976.7
#Mann= 3 ,-1,0
       0      .1       0   366.2    .045       0  381.02      .1       0
Bank Sta=366.2,381.02
XS Rating Curve= 0 ,0
Exp/Cntr(USF)=0,0
Exp/Cntr=0.3,0.1

Type RM Length L Ch R = 1 ,17003   ,248.9,255.2,257
XS GIS Cut Line= 6
1617935.66786809377370.600543842 1618032.2874255377382.979456082
1618121.26231317377380.0280184151618296.62941651377360.782322004
 1618371.9521005377378.0588622541618547.38974176377449.102027252
#Sta/Elev= 30
       0 1023.64    32.7 1008.13      69  998.98    77.1  994.93    93.2  984.08
   101.2  979.41   125.3  969.26   141.3  960.87   157.3  949.94   177.3  940.12
   189.3  933.03   201.4  923.68   213.4     919   225.5  912.02   237.5  911.23
   245.6  908.87   253.6  903.08   273.7  881.96   285.8  870.24   293.9  860.65
   297.9  858.16   300.3 857.614     310  856.63   319.5  857.58   326.1  859.22
   395.2  860.72   419.8  862.99   517.5  868.23   545.6  870.46   629.4  874.62
#Mann= 5 ,-1,0
       0      .1       0   300.3    .045       0   319.5      .1       0
  412.87     .05       0  432.87      .1       0
Bank Sta=300.3,319.5
XS Rating Curve= 0 ,0
Exp/Cntr(USF)=0,0
Exp/Cntr=0.3,0.1

Type RM Length L Ch R = 1 ,16748   ,413.1,401.7,386.5
XS GIS Cut Line= 2
1618056.18549761 377559.06376245 1618558.4653438377703.643249093
#Sta/Elev= 30
       0  928.46    12.4  921.53    24.9  915.52    33.2  910.26    37.4  909.37
    49.6  909.18      54  907.01    65.8   897.7    83.2  880.71    88.4  875.53
     104  857.16  107.19 854.956   112.3  853.58   124.8  854.88   145.6  857.07
   216.4  856.39   266.3  856.87   295.5  859.46   313.4  863.75   324.3  867.94
   332.9  872.31   366.8  898.29   374.5  902.27   398.7  909.94     412  916.46
   416.2  918.71   453.6  943.49   486.9  963.11   507.7  971.81   522.7  980.46
#Mann= 3 ,-1,0
       0      .1       0  107.19    .045       0   124.8      .1       0
#XS Ineff= 2 , 0
                          244.47          864.11
Permanent Ineff=
       F       F
Bank Sta=107.19,124.8
XS Rating Curve= 0 ,0
Exp/Cntr(USF)=0,0
Exp/Cntr=0.3,0.1

Type RM Length L Ch R = 1 ,16346   ,331.4,342.6,354
BEGIN DESCRIPTION:
Low water crossing
END DESCRIPTION:
XS GIS Cut Line= 6
1618001.42469803377956.389610929 1618231.6809175377996.015099861
1618255.24201902377888.9191838291618260.59681483377843.938899095
1618257.38393735377743.2687380251618528.33660491377767.900798712
#Sta/Elev= 30
       0  924.82    10.8  918.23    27.1  911.69    35.2  906.86    47.4  904.18
    57.9   898.6    67.7  892.26      88  874.32   104.2   863.7   120.4  857.36
   132.6  854.27   165.1  851.53   213.9   850.4   327.6  851.85     361  849.63
   367.9   849.3   375.9  849.74   408.6  852.04   548.3  853.72   564.4  855.13
   580.5  864.08   616.6  891.19   632.3  901.71   664.8  915.75   688.9  938.72
     703  949.83   713.9     957   729.5   965.8   753.2  975.08   761.4  979.25
#Mann= 3 ,-1,0
       0      .1       0     361    .045       0   375.9      .1       0
#XS Ineff= 2 , 0
           240.1   860.7  452.96          864.45
Permanent Ineff=
       F       F
Bank Sta=361,375.9
XS Rating Curve= 0 ,0
Exp/Cntr(USF)=0,0
Exp/Cntr=0.3,0.1

Type RM Length L Ch R = 1 ,16003   ,502.4,500,491.6
XS GIS Cut Line= 6
1617986.76291026378152.1206343321618082.85753433378131.831961006
1618170.48760842378136.9208615871618343.83371842   378160.922454
1618418.87457883378165.795147672 1618605.3673161378160.935905427
#Sta/Elev= 30
       0  938.53    17.7  919.77      21  918.01    43.7  908.97    54.5  906.34
      75  896.68    91.3  885.07   107.5  876.22   175.6  852.98   199.7  849.25
   252.2  847.72   268.7  845.85   296.7  847.35  303.62845.4808   308.8  844.81
   320.9  845.47   341.1  851.61   353.2  857.24   369.3  869.42   389.3  890.02
   397.3  896.38     457  917.64   461.8  921.32   473.3  934.07   517.5   964.2
   549.5  976.79   577.5  995.73   593.5 1001.83   609.5 1005.83   622.8 1015.76
#Mann= 3 ,-1,0
       0      .1       0  303.62    .045       0   320.9      .1       0
Bank Sta=303.62,320.9
XS Rating Curve= 0 ,0
Exp/Cntr(USF)=0,0
Exp/Cntr=0.3,0.1

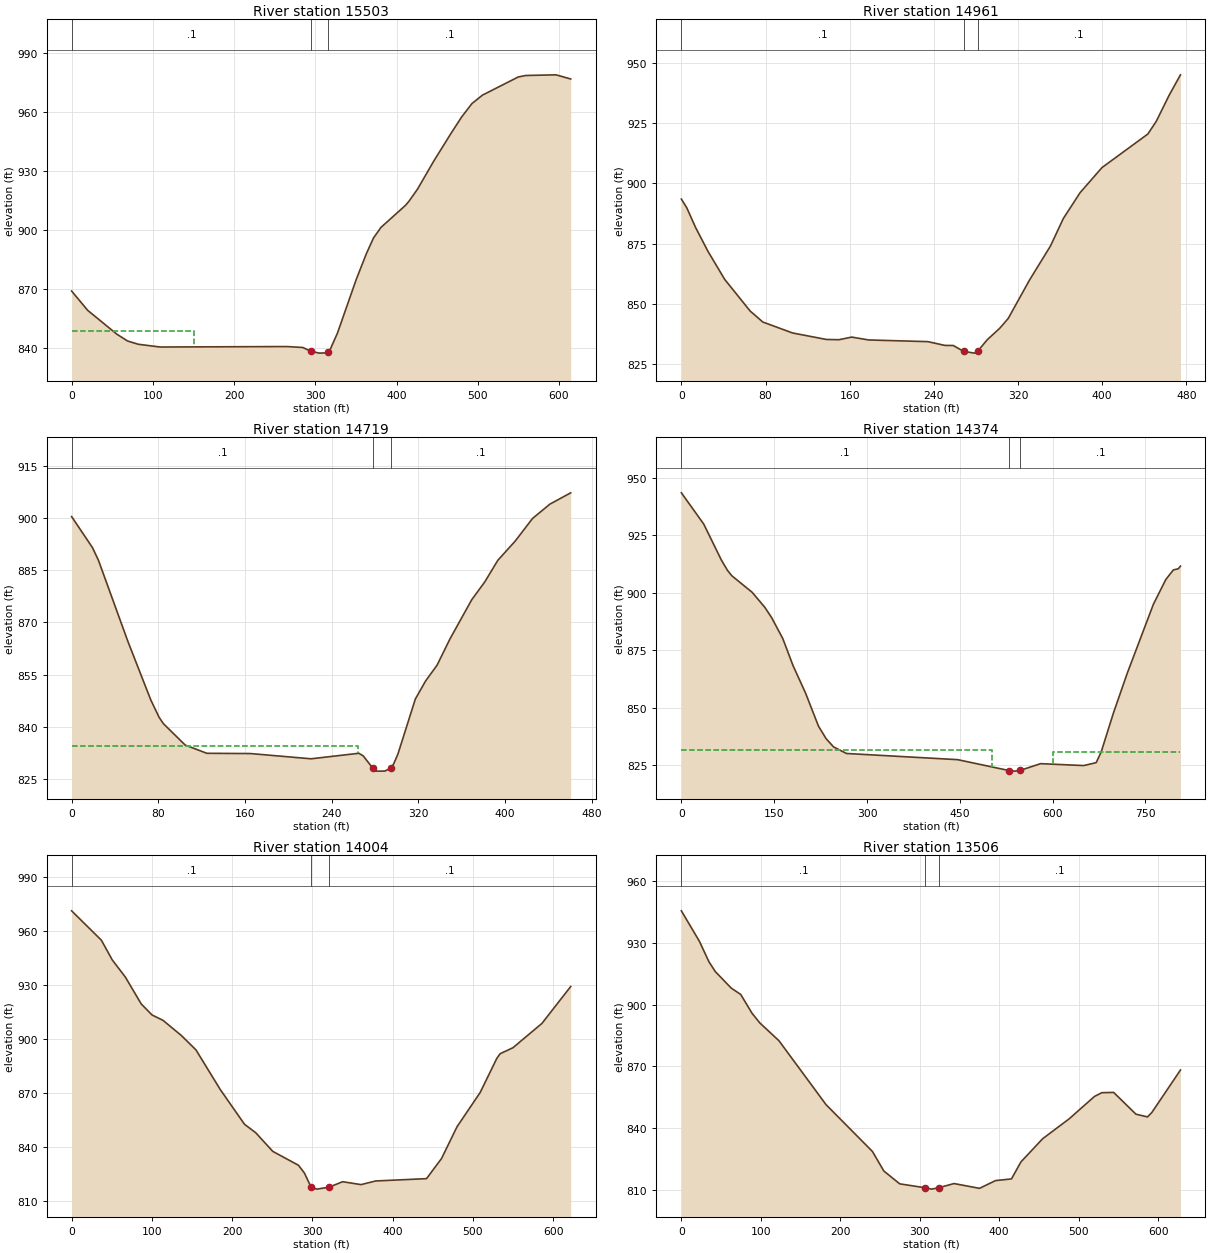
Type RM Length L Ch R = 1 ,15503   ,536.6,542.8,545.2
XS GIS Cut Line= 6
1618162.31866151378747.6246926781618325.02109201378667.752805173
1618482.11329751378590.6358334271618550.59839676378559.865225673
 1618633.0326151378528.4870075881618721.68401259378494.819752082
#Sta/Elev= 30
       0  869.11    19.8   859.3    55.5  847.24    68.8  843.72    82.2  842.04
   108.9  840.65   264.9  840.88   284.6  840.41  294.77838.4399     305  837.54
   313.9  837.68  316.11838.3513   318.4  839.47   327.3  847.76   350.3  874.91
   362.8  888.05   371.6  896.08   380.9  901.51   411.1  912.73   415.5   914.9
   425.9  920.99   445.8   935.2   467.2  949.39     480  957.56   492.9   964.5
   505.7  968.74   549.8  977.99   559.1  978.75   596.3  979.09   614.4  976.98
#Mann= 3 ,-1,0
       0      .1       0  294.77    .045       0  316.11      .1       0
#XS Ineff= 2 , 0
          151.16  848.62
Permanent Ineff=
       F       F
Bank Sta=294.77,316.11
XS Rating Curve= 0 ,0
Exp/Cntr(USF)=0,0
Exp/Cntr=0.3,0.1

Type RM Length L Ch R = 1 ,14961   ,240.8,241.4,241.6
XS GIS Cut Line= 2
1618247.08445283379122.3615021641618718.93429937379073.516231856
#Sta/Elev= 30
       0  893.45     5.1  889.87    13.5  881.67    25.2  871.81    41.2  860.09
    65.4  846.95    77.4   842.4   105.6  837.86   137.8  835.16   149.8  835.05
   161.9  836.14     178  834.95   234.3  834.25   250.4  832.69   258.4  832.65
   268.3  830.22   278.5  829.48   281.7  830.28   290.6  834.98   302.6   839.8
   310.7   843.9   330.8  859.74   350.9  874.03     363  885.34     379  896.13
   399.8  906.54   443.4  920.48   451.4  925.75   463.5  936.47   474.4  945.07
#Mann= 3 ,-1,0
       0      .1       0   268.3    .045       0   281.7      .1       0
Bank Sta=268.3,281.7
XS Rating Curve= 0 ,0
Exp/Cntr(USF)=0,0
Exp/Cntr=0.3,0.1

Type RM Length L Ch R = 1 ,14719   ,329.9,344.7,357.6
BEGIN DESCRIPTION:
Structure 12 XS 4
END DESCRIPTION:
XS GIS Cut Line= 2
1618259.48252425379348.0649205991618719.24529178379323.968339492
#Sta/Elev= 30
       0  900.48    19.2  891.57    24.7  887.95    51.9  864.55      73  847.73
    80.7   842.7    84.7  840.85   104.8   834.7   124.8  832.33   164.9  832.26
   220.9  830.75     265  832.34     269  831.59     278     828     281   827.2
     289  827.21  294.23828.0704     297  829.22     301   832.1   317.1  847.96
   326.6  853.18   337.1  857.68   349.1   865.3   369.1  876.54   381.2   881.7
   393.2   887.9   409.2  893.42   425.2  899.94   441.2  904.06   460.4  907.32
#Mann= 3 ,-1,0
       0      .1       0     278    .045       0  294.23      .1       0
#XS Ineff= 2 , 0
          264.14  834.37
Permanent Ineff=
       F       F
Bank Sta=278,294.23
XS Rating Curve= 0 ,0
Exp/Cntr(USF)=0,0
Exp/Cntr=0.3,0.1

Type RM Length L Ch R = 1 ,14374   ,389.1,370.7,350.7
BEGIN DESCRIPTION:
Structure 12 XS low water crossing
END DESCRIPTION:
XS GIS Cut Line= 4
1618113.06079715379393.342450136 1618458.1238386379479.126278878
1618508.24472731379745.1525343011618687.52329074379724.911406171
#Sta/Elev= 30
       0  943.47    36.1   929.9    64.6  914.28    74.5  909.78    81.5  907.44
   114.4  900.24     135  893.67   145.9  889.22   163.9  880.15   180.4  868.44
     201  856.27   221.6  842.08     234  836.62   246.1  833.04   266.9  830.21
   446.6  827.52   529.7  822.79   539.2  822.54   547.9822.8885   580.5  825.78
   650.3  824.96   670.4  826.22   678.5  830.82   698.6     848   720.7  865.07
     763  895.08   783.1  905.83   795.2  909.96   803.3  910.48   806.7  911.62
#Mann= 3 ,-1,0
       0      .1       0   529.7    .045       0   547.9      .1       0
#XS Ineff= 2 , 0
          501.61  831.52  600.26          831.04
Permanent Ineff=
       F       F
Bank Sta=529.7,547.9
XS Rating Curve= 0 ,0
Exp/Cntr(USF)=0,0
Exp/Cntr=0.3,0.1

Type RM Length L Ch R = 1 ,14004   ,492.4,497.7,503.7
BEGIN DESCRIPTION:
Structure 12 XS 1
END DESCRIPTION:
XS GIS Cut Line= 6
1618171.12868325380113.8197949231618254.43265051380070.763450593
1618397.09082976379992.9502860011618550.08789909379907.445863843
  1618636.122832379880.4278732541618735.72269842379872.167391092
#Sta/Elev= 30
       0  971.24    37.1  954.91    50.6  943.99      67  934.41    86.7  919.54
   100.2   913.4   113.9   910.4   136.7     902   154.9  894.01   185.1  872.04
   215.4  852.68   229.3  848.03   250.6  837.64   282.6  829.93     290   825.6
   298.2  817.88   305.5  816.68   320.6  817.75   337.6   820.8   360.5  819.18
   378.8  821.21   442.1   822.5   460.8  833.67   480.1  851.32   508.9  870.32
   529.7  889.32   533.8  891.88   549.8  895.22   585.9  908.73   621.7  929.19
#Mann= 3 ,-1,0
       0      .1       0   298.2    .045       0   320.6      .1       0
Bank Sta=298.2,320.6
XS Rating Curve= 0 ,0
Exp/Cntr(USF)=0,0
Exp/Cntr=0.3,0.1

Type RM Length L Ch R = 1 ,13506   ,497.2,499.9,501.7
XS GIS Cut Line= 6
1618265.43426892380434.3785369991618369.26608226380434.315873086
1618462.00769468380432.8526214211618537.16436851380436.308651254
1618636.75308008380445.3844204991618891.81195317380470.066457748
#Sta/Elev= 30
       0  945.44    22.7  930.66    34.7  920.75    42.7  915.99    62.7     908
    74.7   904.9    88.9  895.81    98.7  891.11   122.7  882.53   182.1  851.48
   240.4  828.83   254.8  819.34   274.8  813.12   306.9  811.21   314.9  810.56
  324.03811.2465   343.1  813.26   375.2  810.94   395.3  814.69   415.4  815.51
   427.4  823.78   454.7  834.99   487.7  844.53   519.9  855.48   529.1  857.29
     544  857.44   572.1  846.88   586.6  845.56   592.2  847.77   628.1  868.28
#Mann= 3 ,-1,0
       0      .1       0   306.9    .045       0  324.03      .1       0
Bank Sta=306.9,324.03
XS Rating Curve= 0 ,0
Exp/Cntr(USF)=0,0
Exp/Cntr=0.3,0.1

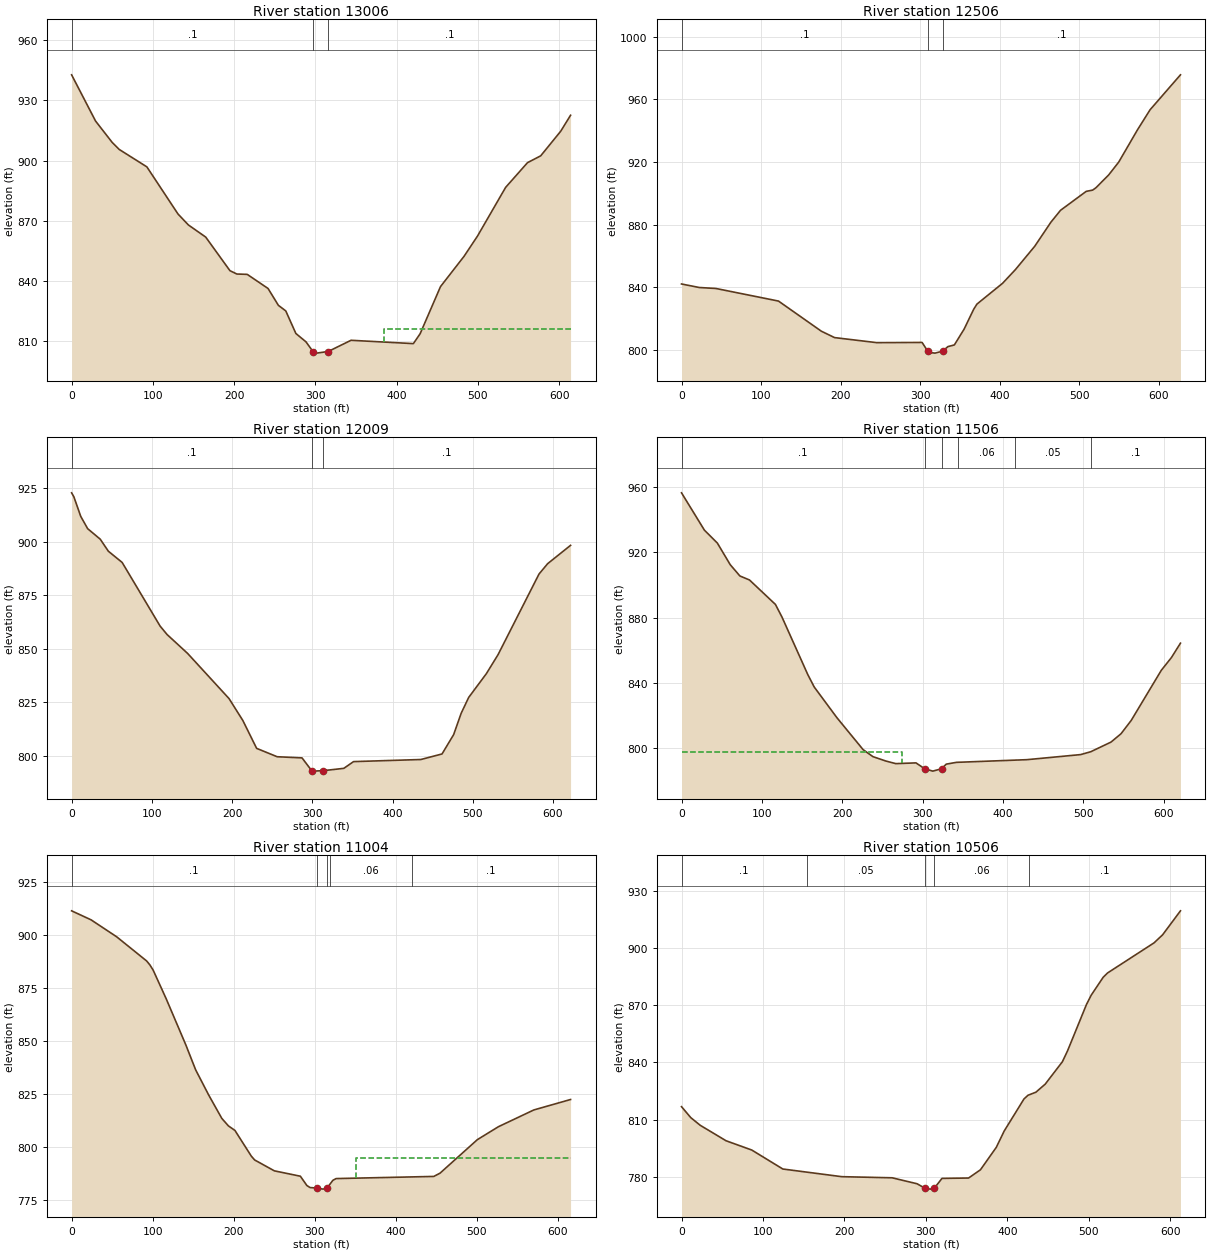
Type RM Length L Ch R = 1 ,13006   ,499.3,500,496
XS GIS Cut Line= 6
1618137.13924992380801.6586423371618307.38989368380863.838308007
1618471.76981425380923.8732929231618542.21849225380949.602244094
1618627.25145867380971.8292337511618720.02883217380990.917778254
#Sta/Elev= 30
       0  942.78    29.5  919.72      50  909.05    58.5   905.6    92.6  896.89
   130.9  873.39   143.7  867.93     165  861.88   194.8  845.14   203.3  843.47
   216.1  843.29   241.7  836.26   254.4  827.86   263.5  825.08   275.9  813.84
   288.4  809.64     297  804.81   301.3  804.03  315.64 804.838   343.8  810.43
   420.5  808.77   428.8  813.69   453.9  837.21   482.8  852.27   499.4  862.39
     534  886.66   560.9  898.98   577.2  902.41   601.8  914.67   613.9  922.62
#Mann= 3 ,-1,0
       0      .1       0     297    .045       0  315.64      .1       0
#XS Ineff= 2 , 0
                          383.74             816
Permanent Ineff=
       F       F
Bank Sta=297,315.64
XS Rating Curve= 0 ,0
Exp/Cntr(USF)=0,0
Exp/Cntr=0.3,0.1

Type RM Length L Ch R = 1 ,12506   ,501.3,497.3,491.6
XS GIS Cut Line= 6
1618114.49625058381399.5166985841618298.82495017381348.858335346
1618374.96160892381333.0617790071618473.48240925381350.197571501
1618635.30295175381374.0682586731618729.84902251381384.530180007
#Sta/Elev= 30
       0  841.97    22.4  839.71    43.2   839.1     122  831.04   175.9  811.77
   192.5  807.68   245.6  804.45   302.6  804.59  309.56799.1384   310.7  798.23
   318.8  797.75   328.3  798.99   335.1  801.91   343.2  802.99   355.4  813.04
   367.5  825.79   371.6  829.11   403.9  842.43   420.1  851.23   444.3   866.1
   464.6  881.46   476.7  889.07     509  901.19   517.1     902   521.2  903.47
   537.3   911.7     550  919.97   573.6  940.62   589.4   953.4   627.6  975.73
#Mann= 3 ,-1,0
       0      .1       0  309.56    .045       0   328.3      .1       0
Bank Sta=309.56,328.3
XS Rating Curve= 0 ,0
Exp/Cntr(USF)=0,0
Exp/Cntr=0.3,0.1

Type RM Length L Ch R = 1 ,12009   ,493.6,502.5,508.2
XS GIS Cut Line= 6
1618197.48230509381944.1287983361618435.98674934381850.429182589
1618528.43374293381808.2498050031618593.45296983381766.117015257
1618670.01384035381718.6499185861618754.56452426381672.159197927
#Sta/Elev= 30
       0  922.92     2.8  921.08    11.4  911.89      20  906.16    35.7  901.23
    45.8  895.61      63  890.36   110.3   860.6   118.9  856.69   144.6  847.81
   196.2   826.7   213.4  816.47   230.6  803.42   256.2   799.5   287.2  798.96
   299.4  792.92   300.4  792.77   313.5  792.98   339.3  794.07   351.4  797.22
   435.3   798.2   461.7   800.8   476.2  809.86   485.5  819.78   494.9  827.22
   516.9  838.32   531.5  847.22   582.6  884.95   593.3  889.77   621.9  898.36
#Mann= 3 ,-1,0
       0      .1       0   299.4    .045       0   313.5      .1       0
Bank Sta=299.4,313.5
XS Rating Curve= 0 ,0
Exp/Cntr(USF)=0,0
Exp/Cntr=0.3,0.1

Type RM Length L Ch R = 1 ,11506   ,503.8,502,499.2
XS GIS Cut Line= 6
  1618335.658866382244.3814786671618432.71346192382250.825363427
1618522.48460785382261.3342006651618598.05630709382274.775446758
1618693.80841218382304.1146269291618938.90864375382378.463231504
#Sta/Elev= 30
       0  956.46    28.5  933.59    44.6  925.69    60.6  912.47    72.6  905.57
    84.6  903.09   116.8  888.16   124.9   880.5   157.1  845.19   165.1  837.58
   193.4  818.75   225.9  799.25   238.1  794.97   254.3  792.25   266.6  790.68
   291.7  791.13   302.7  787.49   312.6  786.09  323.47787.5384   329.3  790.36
   341.9  791.46   429.7   793.1   496.5  796.21   509.1  797.96   534.2  803.84
   546.7  808.95   559.4   817.1   596.9  847.84   609.4  855.58   620.7  864.42
#Mann= 6 ,-1,0
       0      .1       0   302.7    .045       0  323.47     .05       0
  344.41     .06       0  414.56     .05       0  509.53      .1       0
#XS Ineff= 2 , 0
          274.87     798
Permanent Ineff=
       F       F
Bank Sta=302.7,323.47
XS Rating Curve= 0 ,0
Exp/Cntr(USF)=0,0
Exp/Cntr=0.3,0.1

Type RM Length L Ch R = 1 ,11004   ,501,498.2,494.6
XS GIS Cut Line= 6
1618224.10331485 382802.78620176  1618318.489609382793.373162836
1618406.31522076 382781.752779261618481.15791884382769.986398593
1618581.11178717382763.0835252551618837.10635392 382754.70263651
#Sta/Elev= 30
       0  911.29      24  907.04    55.5  899.06    92.5  887.65    96.5   885.8
   100.5  883.39   116.7  869.77   140.9  848.03     153  836.28   169.1  824.37
   185.3  813.34   193.4  809.82   201.5  807.66   221.7  795.53   225.8  793.73
   250.1   788.6   282.2  786.06   290.2  781.68   294.2  780.71   302.3  780.47
   310.3  779.97  315.15 780.496   322.3  784.13   326.3  784.95   446.8  785.96
   454.5  787.51   500.5  803.31   526.5  809.42   570.2  817.33   615.5  822.26
#Mann= 5 ,-1,0
       0      .1       0   302.3    .045       0  315.15      .1       0
  319.21     .06       0   419.4      .1       0
#XS Ineff= 2 , 0
                           350.9          794.48
Permanent Ineff=
       F       F
Bank Sta=302.3,315.15
XS Rating Curve= 0 ,0
Exp/Cntr(USF)=0,0
Exp/Cntr=0.3,0.1

Type RM Length L Ch R = 1 ,10506   ,351.9,360.3,365.7
XS GIS Cut Line= 6
1618486.79373434383367.2325794251618564.23682092383314.243840262
1618635.54343684383263.5185480121618697.05906184 383220.61213775
1618913.02614959383071.3998377621618990.15755701383018.109918088
#Sta/Elev= 30
       0  816.87    11.3  811.15      23   807.1    54.7  799.01    86.3  794.15
   124.4  784.22   196.7  780.21   258.6  779.62   289.2   776.5   298.8  774.19
   305.7  773.69   310.4  774.19   319.8  779.31   352.4   779.5     367   783.8
   386.5  795.58   396.2  804.14   420.5  820.91   425.4  822.84   435.1  824.44
   446.5  828.64   467.6  840.37     474  846.13   497.2  870.37     503  875.23
   517.7   884.6   523.1  886.87   580.2  902.64   590.7  906.85   612.6   919.4
#Mann= 5 ,-1,0
       0      .1       0  153.84     .05       0   298.8    .045       0
   310.4     .06       0  426.34      .1       0
Bank Sta=298.8,310.4
XS Rating Curve= 0 ,0
Exp/Cntr(USF)=0,0
Exp/Cntr=0.3,0.1

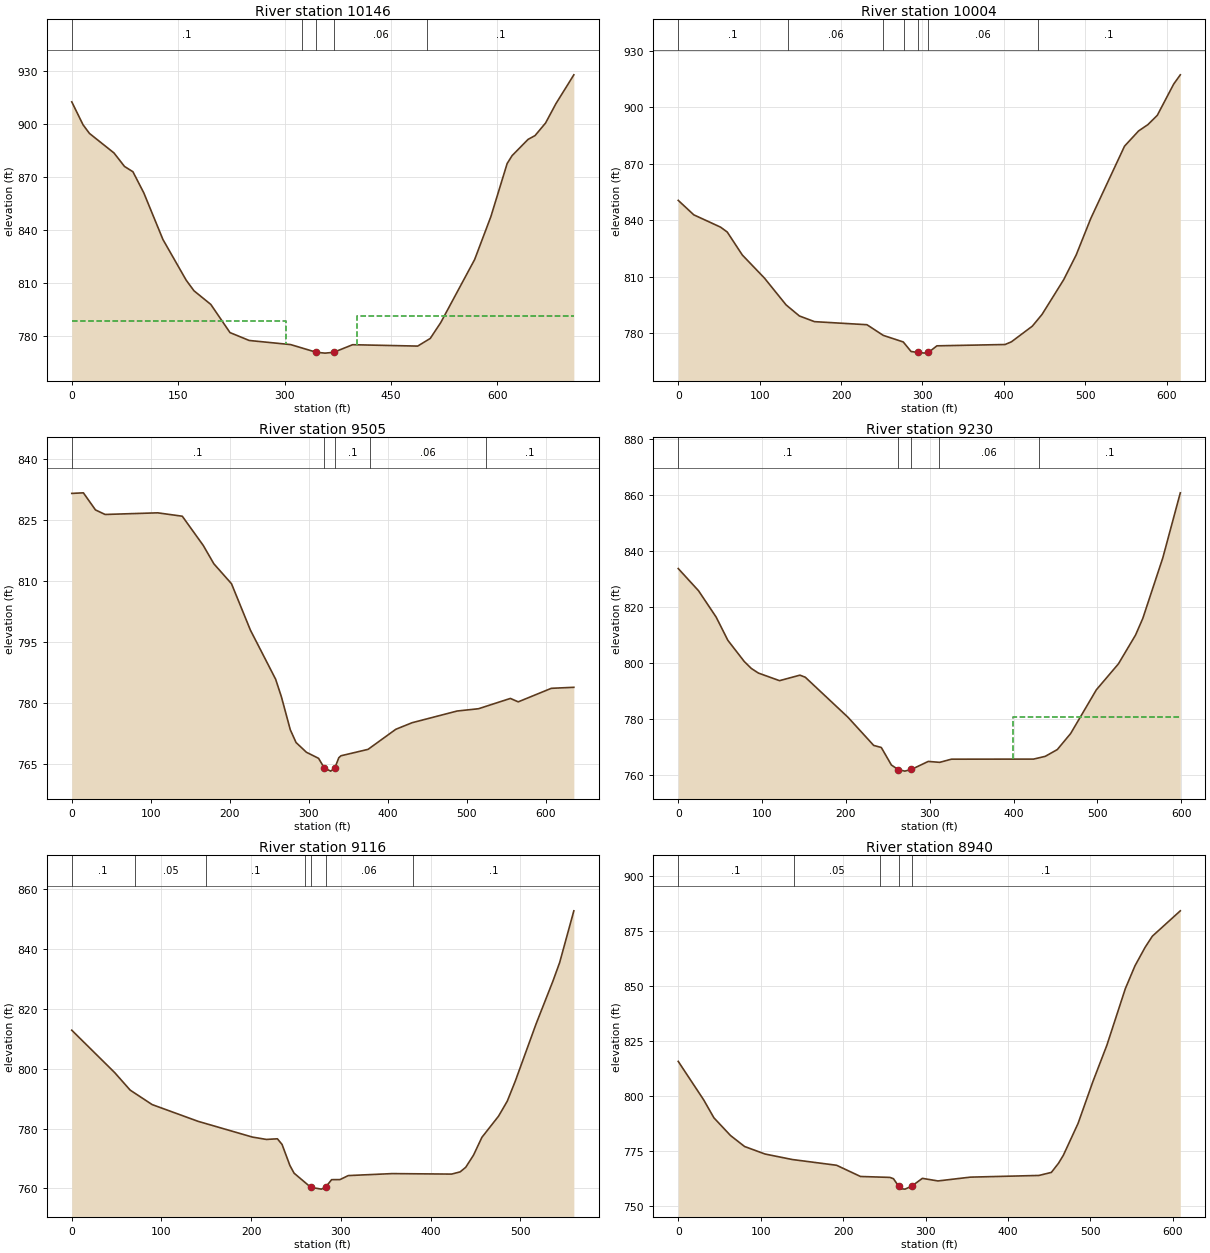
Type RM Length L Ch R = 1 ,10146   ,151.7,141.7,133.6
XS GIS Cut Line= 4
1618545.98703667383642.6011992441618816.28102877 383502.83942772
1618895.39146548383538.439124241 1619152.5003848383353.848105247
#Sta/Elev= 30
       0  912.76    15.9  899.76    24.9  894.88    59.5  883.79    74.3  876.16
    86.2  873.13   101.5  861.18   128.5  834.72   161.3  811.64   172.3  805.64
     196  797.91     223  781.96   250.1  777.49   308.5  775.16   344.8  770.79
   356.9  770.32     369  770.76   395.8  775.09   487.5  774.31   505.2  778.64
     520  787.62   567.8  823.39   590.7  847.75   613.6   877.8   620.6  882.28
   643.1  891.49   652.9  893.63   667.7  900.74   682.4  911.77   707.6  928.08
#Mann= 5 ,-1,0
       0      .1       0  324.29     .06       0   344.8    .045       0
     369     .06       0  501.04      .1       0
#XS Ineff= 2 , 0
          301.41  788.52   401.5           791.3
Permanent Ineff=
       F       F
Bank Sta=344.8,369
XS Rating Curve= 0 ,0
Exp/Cntr(USF)=0,0
Exp/Cntr=0.3,0.1

Type RM Length L Ch R = 1 ,10004   ,496.7,499,500.2
XS GIS Cut Line= 6
1618763.30860126383869.1630060081618826.55683434 383799.26583609
1618878.68435475 383728.984480591619026.00886326383527.005553842
1619089.99725235383465.6926843381619166.53975017 383407.18328692
#Sta/Elev= 30
       0  850.52    19.1  842.85      52  836.32    60.2  833.73    78.7  821.55
   105.9   809.3   132.5  795.06   148.8  789.21   167.4  786.19   231.8  784.56
   251.8  778.91   276.4  775.42     286  770.35   294.8  769.84   303.4  769.49
  307.38769.8441   317.7  773.36   401.4  774.06   409.3   775.5     435  783.82
   446.9  790.05   473.5  808.48   488.8  821.57   506.7   840.9   548.2  879.29
   565.5  887.37   576.9  890.71   588.4  895.62   608.6  912.24   616.7  917.12
#Mann= 7 ,-1,0
       0      .1       0  134.27     .06       0  251.77      .1       0
  276.77     .06       0   294.8    .045       0  307.38     .06       0
  441.77      .1       0
Bank Sta=294.8,307.38
XS Rating Curve= 0 ,0
Exp/Cntr(USF)=0,0
Exp/Cntr=0.3,0.1

Type RM Length L Ch R = 1 ,9505    ,268.6,275,277.3
XS GIS Cut Line= 6
1618983.66610017384151.2634916751619078.03828676384112.294737592
1619163.78745909384071.3276279271619233.26041725384030.070820674
 1619312.2576346383966.7093988361619510.06366943383803.808149844
#Sta/Elev= 30
       0  831.51    14.7  831.65      30  827.46    42.2  826.34   108.8  826.74
   139.9  825.91   166.5  818.72   179.8  814.25   202.2  809.34   226.1  797.97
     258  785.93   265.3  781.63   276.6  773.51   283.9  770.38     297  767.99
   312.4   766.5  319.64764.1411   327.7  763.36   332.9  764.08     338  766.65
   340.8  767.13     375   768.7   410.1  773.62   430.8  775.24   487.8  778.11
   514.8  778.67   555.2   781.2   565.1  780.36     607  783.68   635.5  783.93
#Mann= 5 ,-1,0
       0      .1       0  319.64    .045       0   332.9      .1       0
  377.93     .06       0   524.2      .1       0
Bank Sta=319.64,332.9
XS Rating Curve= 0 ,0
Exp/Cntr(USF)=0,0
Exp/Cntr=0.3,0.1

Type RM Length L Ch R = 1 ,9230    ,119,114.2,111.8
XS GIS Cut Line= 4
1619029.07755547384339.9596988561619251.11286266384268.831505209
1619318.39628909384266.9091215961619574.07330949384113.118432629
#Sta/Elev= 30
       0  833.73    24.2  825.82    45.2  816.43    59.2  808.13    78.8  800.56
    87.2   798.1    95.6  796.46   120.8  793.75   145.1  795.71   151.5  794.98
   202.4  780.71   233.1  770.66   242.2  769.92   254.2  763.68   262.2  762.07
   270.2  761.49   278.2  762.11   298.2  764.95   311.8  764.62   325.8  765.75
   423.8  765.78   437.8  766.77   452.1  769.18     468   774.9   498.7   790.5
     525  799.75   545.4  810.01   554.1  815.98   577.9  837.52   598.8  860.73
#Mann= 5 ,-1,0
       0      .1       0   262.2    .045       0   278.2      .1       0
  310.46     .06       0  430.46      .1       0
#XS Ineff= 2 , 0
                          398.71          780.62
Permanent Ineff=
       F       F
Bank Sta=262.2,278.2
XS Rating Curve= 0 ,0
Exp/Cntr(USF)=0,0
Exp/Cntr=0.3,0.1

Type RM Length L Ch R = 1 ,9116    ,178.6,176.4,171.5
BEGIN DESCRIPTION:
Structure 11 XS 4
END DESCRIPTION:
XS GIS Cut Line= 2
1619103.02742154384496.6049765771619584.29795778384211.015867158
#Sta/Elev= 30
       0  812.83    47.8  798.69    65.1  792.83    89.6     788   140.8  782.41
   201.3  777.16   216.9  776.37   229.2  776.58   234.4  774.69   243.1  767.69
   247.8   765.1   266.5  760.37   278.2  759.78   282.9760.4318   289.6  762.94
   298.9  762.96   308.2   764.3     357  764.96   423.4   764.8   432.9  765.54
   439.1  767.07   447.8  771.14   457.1  777.06   475.7  784.15   485.4  789.15
   494.3   795.8   517.5  814.93   536.2  829.15   543.8  835.43   559.6  852.68
#Mann= 7 ,-1,0
       0      .1       0      70     .05       0     150      .1       0
     260     .06       0   266.5    .045       0   282.9     .06       0
     380      .1       0
Bank Sta=266.5,282.9
XS Rating Curve= 0 ,0
Exp/Cntr(USF)=0,0
Exp/Cntr=0.3,0.1

Type RM Length L Ch R = 1 ,8940    ,46.3,46.4,45.9
BEGIN DESCRIPTION:
Structure 11 XS 3
END DESCRIPTION:
XS GIS Cut Line= 4
1619194.25727594384593.1235181861619411.09345161384536.270130663
1619523.47805485384348.5217346561619671.56129677384273.157941893
#Sta/Elev= 30
       0  815.77    30.9  798.26    43.3  790.11    63.4  782.07    80.5  777.07
   105.3  773.65   138.4  771.15   192.1  768.54   221.1  763.44   256.8  763.02
   261.1  762.43   267.4759.0156   270.5  757.85   275.1  757.69     283  758.98
   296.2  762.59   315.1  761.41   354.4  763.14   437.6  763.91   452.7   765.3
   461.3  769.44   467.2  773.08   485.1   787.6   502.9  806.44     520  823.11
   542.4  848.84   554.1  859.23   566.4  867.64   575.2  872.71   609.1  884.23
#Mann= 5 ,-1,0
       0      .1       0     140     .05       0  244.17      .1       0
   267.4    .045       0     283      .1       0
Bank Sta=267.4,283
XS Rating Curve= 0 ,0
Exp/Cntr(USF)=0,0
Exp/Cntr=0.3,0.1

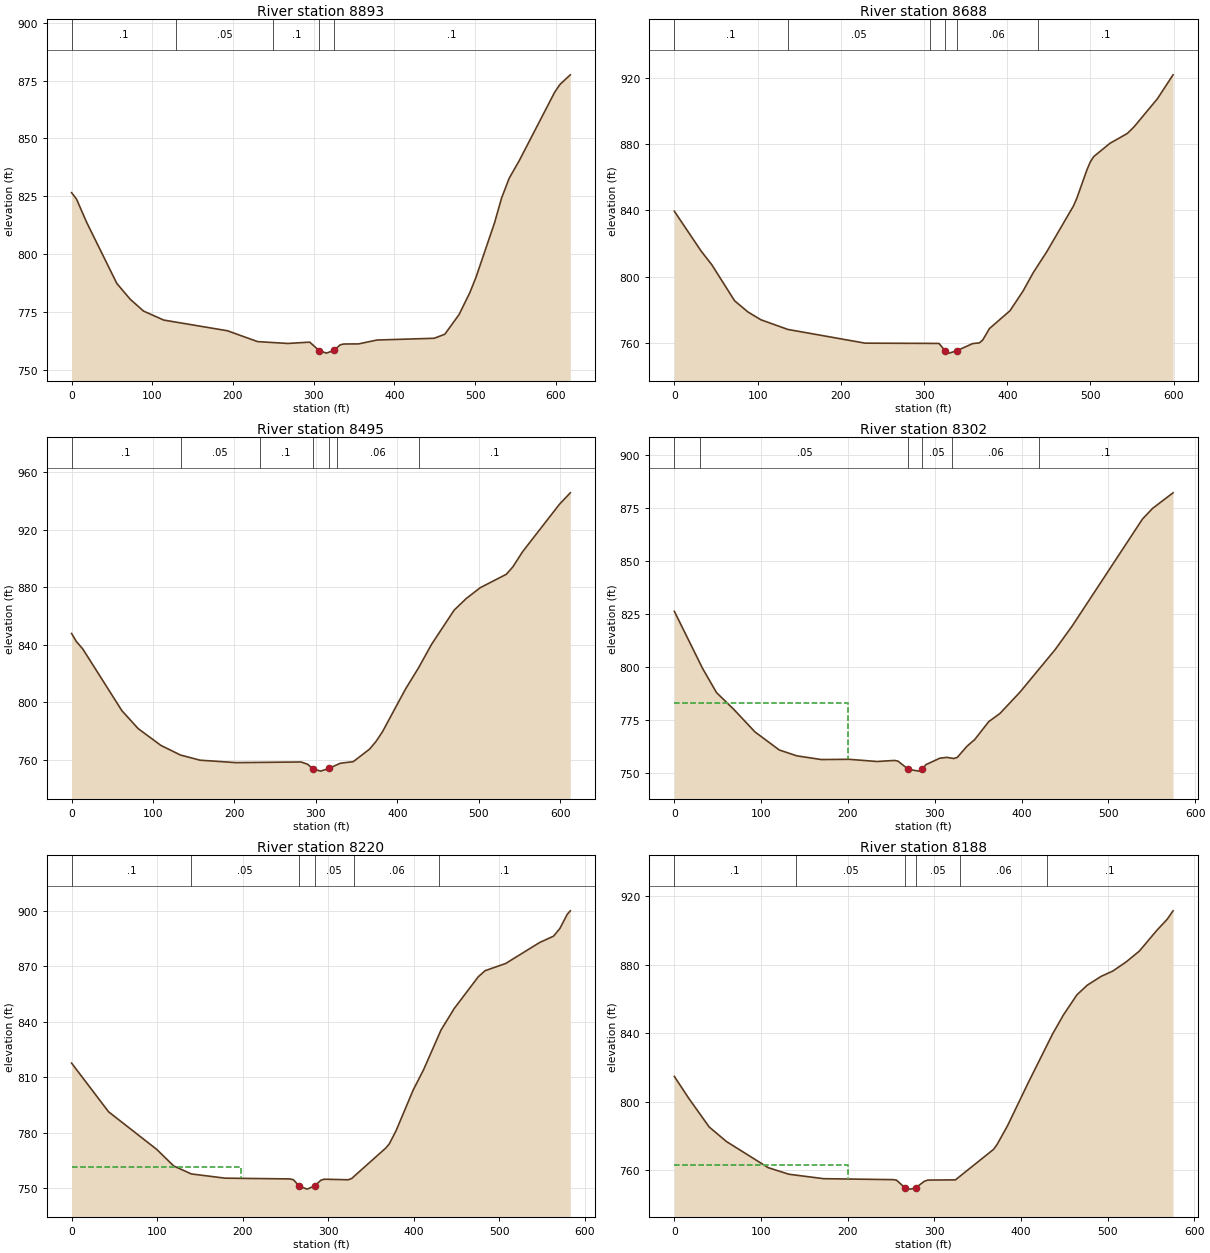
Type RM Length L Ch R = 1 ,8893    ,192.7,204.9,213.4
BEGIN DESCRIPTION:
Structure 11 XS 2
END DESCRIPTION:
XS GIS Cut Line= 5
1619198.22379135384626.177813258 1619456.0472929  384553.4583641
1619527.44457026 384423.88552742 1619548.5993191384386.864716939
 1619684.7830148384303.567893359
#Sta/Elev= 30
       0  826.55     6.1  823.81    18.6   813.8      56  787.39    72.6  780.54
    89.2  775.41   114.2  771.53   193.1  766.92   230.5  762.23   267.9  761.43
   295.1     762   306.9  758.34   315.7  757.25  324.95758.3862   332.9  760.83
   337.4  761.19   355.7  761.24   378.5  762.91   449.4  763.67   462.6  765.42
   480.2   773.9   493.6  783.39   501.3   790.1   524.3  813.66   532.9  824.22
   542.3  832.78   554.9  840.46   598.6  869.89   605.3  873.34   618.1  877.49
#Mann= 5 ,-1,0
       0      .1       0     130     .05       0     250      .1       0
   306.9    .045       0  324.95      .1       0
Bank Sta=306.9,324.95
XS Rating Curve= 0 ,0
Exp/Cntr(USF)=0,0
Exp/Cntr=0.3,0.1

Type RM Length L Ch R = 1 ,8688    ,194.4,193.3,192.3
BEGIN DESCRIPTION:
Structure 11 XS 1
END DESCRIPTION:
XS GIS Cut Line= 3
1619194.25727594384660.5542801331619274.90975591384628.822156864
1619782.62372821384698.897262416
#Sta/Elev= 30
       0  839.55    32.1  815.57      45  807.28    72.4  785.53    88.4   778.8
     104  774.08   136.3  768.26   229.2  759.98     318  759.81  325.37 755.391
   330.2  753.96   339.4  755.41   358.4  759.71   366.5  760.15   370.5  761.84
   378.6  768.78   403.3  779.55     419  791.44   431.1  802.41   447.3  814.98
   479.6  842.78   483.6  847.39   495.7  864.48   499.8  869.32   503.8  872.47
   523.4  880.53   544.2  886.43   552.2  890.37   580.3  907.33   599.2  921.83
#Mann= 6 ,-1,0
       0      .1       0  136.67     .05       0  306.67      .1       0
  325.37    .045       0   339.4     .06       0  436.67      .1       0
Bank Sta=325.37,339.4
XS Rating Curve= 0 ,0
Exp/Cntr(USF)=0,0
Exp/Cntr=0.3,0.1

Type RM Length L Ch R = 1 ,8495    ,191.9,192.9,193.5
BEGIN DESCRIPTION:
Structure 10 XS 4
END DESCRIPTION:
XS GIS Cut Line= 6
1619194.29756868384849.6653100851619375.52391225384852.588204503
1619450.51424783 384853.797191591619550.50125259384855.409393087
1619625.49158818384856.6190363321619806.71793176384859.541274592
#Sta/Elev= 30
       0  847.93     5.8  842.35    13.8  837.11    61.8   794.2    81.8  781.73
   109.8  770.03   133.8  763.36   157.8  759.79   201.8  758.09   281.9  758.54
   289.9  756.96     296  753.88   305.9  752.18  315.94754.0344   329.9  757.65
   345.9  758.76   365.9  767.46   373.9  772.84   381.9  779.65   410.1  809.27
   426.2  824.11   442.1  840.38   469.9  864.21   484.9  872.33   501.9  879.78
   533.9  889.09   541.9  894.23   553.9  904.79   599.1  937.75   612.5  945.76
#Mann= 7 ,-1,0
       0      .1       0  133.75     .05       0  231.25      .1       0
     296    .045       0  315.94      .1       0  326.25     .06       0
  426.25      .1       0
Bank Sta=296,315.94
XS Rating Curve= 0 ,0
Exp/Cntr(USF)=0,0
Exp/Cntr=0.3,0.1

Type RM Length L Ch R = 1 ,8302    ,82.5,82.1,81.3
XS GIS Cut Line= 2
1619203.78039908385017.8513724261619775.44831665385075.595606524
#Sta/Elev= 30
       0  826.27    32.5  799.29    48.6  787.82    68.7  779.82    92.8  769.26
   120.9   760.7     141  757.93   169.2  756.17   201.4  756.28   233.5  755.24
   253.6  755.74   257.6  755.44   269.7  751.51   281.8  750.69   285.8  751.58
   289.8  753.74   305.9  756.81   313.9   757.2     322  756.66     326  757.19
   337.2  762.48   346.1  765.63   362.2  774.08   375.2  777.98   398.4  788.13
   438.6  808.09   458.7  819.52   539.5  869.99   551.1  874.98   574.6  882.31
#Mann= 6 ,-1,0
       0      .1       0      30     .05       0   269.7    .045       0
   285.8     .05       0     320     .06       0     420      .1       0
#XS Ineff= 2 , 0
          199.65  783.12
Permanent Ineff=
       F       F
Bank Sta=269.7,285.8
XS Rating Curve= 0 ,0
Exp/Cntr(USF)=0,0
Exp/Cntr=0.3,0.1

Type RM Length L Ch R = 1 ,8220    ,32.2,32.3,32.8
BEGIN DESCRIPTION:
Structure 10 XS 3
END DESCRIPTION:
XS GIS Cut Line= 2
1619192.80311771385115.9446917911619775.74760786385137.631614787
#Sta/Elev= 30
       0  817.57    43.3  791.25    99.4  771.02   119.4  762.02     140  757.69
   179.4  755.41   255.5  754.99   259.5  754.55   266.2  751.13   275.5  749.48
  284.43751.2694   291.5  754.27   295.5  754.84   323.5  754.54   327.5  755.19
   367.6  771.74   371.6  773.94   379.6  781.14   399.6  803.11   411.6  813.92
   432.1  835.48   447.6  847.13   475.6  864.21   483.6  867.52   507.7  871.42
   547.4  882.75   563.7  886.19   571.1  890.33   579.7  897.99   583.3  899.88
#Mann= 6 ,-1,0
       0      .1       0     140     .05       0   266.2    .045       0
  284.43     .05       0     330     .06       0     430      .1       0
#XS Ineff= 2 , 0
           198.2  761.18
Permanent Ineff=
       F       F
Bank Sta=266.2,284.43
XS Rating Curve= 0 ,0
Exp/Cntr(USF)=0,0
Exp/Cntr=0.5,0.3

Type RM Length L Ch R = 1 ,8188    ,192.2,194.3,195.9
BEGIN DESCRIPTION:
Structure 10 XS 2
END DESCRIPTION:
XS GIS Cut Line= 2
1619191.93564079385148.0413378251619767.07283866385169.728260822
#Sta/Elev= 30
       0  814.82    16.2  802.36    40.2  785.31    60.2   776.8   108.3  761.58
   132.3  757.73   172.3  755.14   252.4  754.59   256.4  754.28  266.28  749.74
   272.4  749.05  278.31  749.74   288.4  753.59   292.4  754.33   324.4  754.46
   368.4  772.27   372.4  775.07   384.5  786.05   408.5  811.26   436.5  839.59
   448.9   850.6   464.5  862.39   476.5  868.05   492.5   873.2     506   876.3
   521.4  881.64   536.6  887.93   556.6  899.95   568.6  906.44   575.5  911.44
#Mann= 6 ,-1,0
       0      .1       0     140     .05       0  266.28    .045       0
  278.31     .05       0     330     .06       0     430      .1       0
#XS Ineff= 2 , 0
          200.51  763.32
Permanent Ineff=
       F       F
Bank Sta=266.28,278.31
XS Rating Curve= 0 ,0
Exp/Cntr(USF)=0,0
Exp/Cntr=0.3,0.1