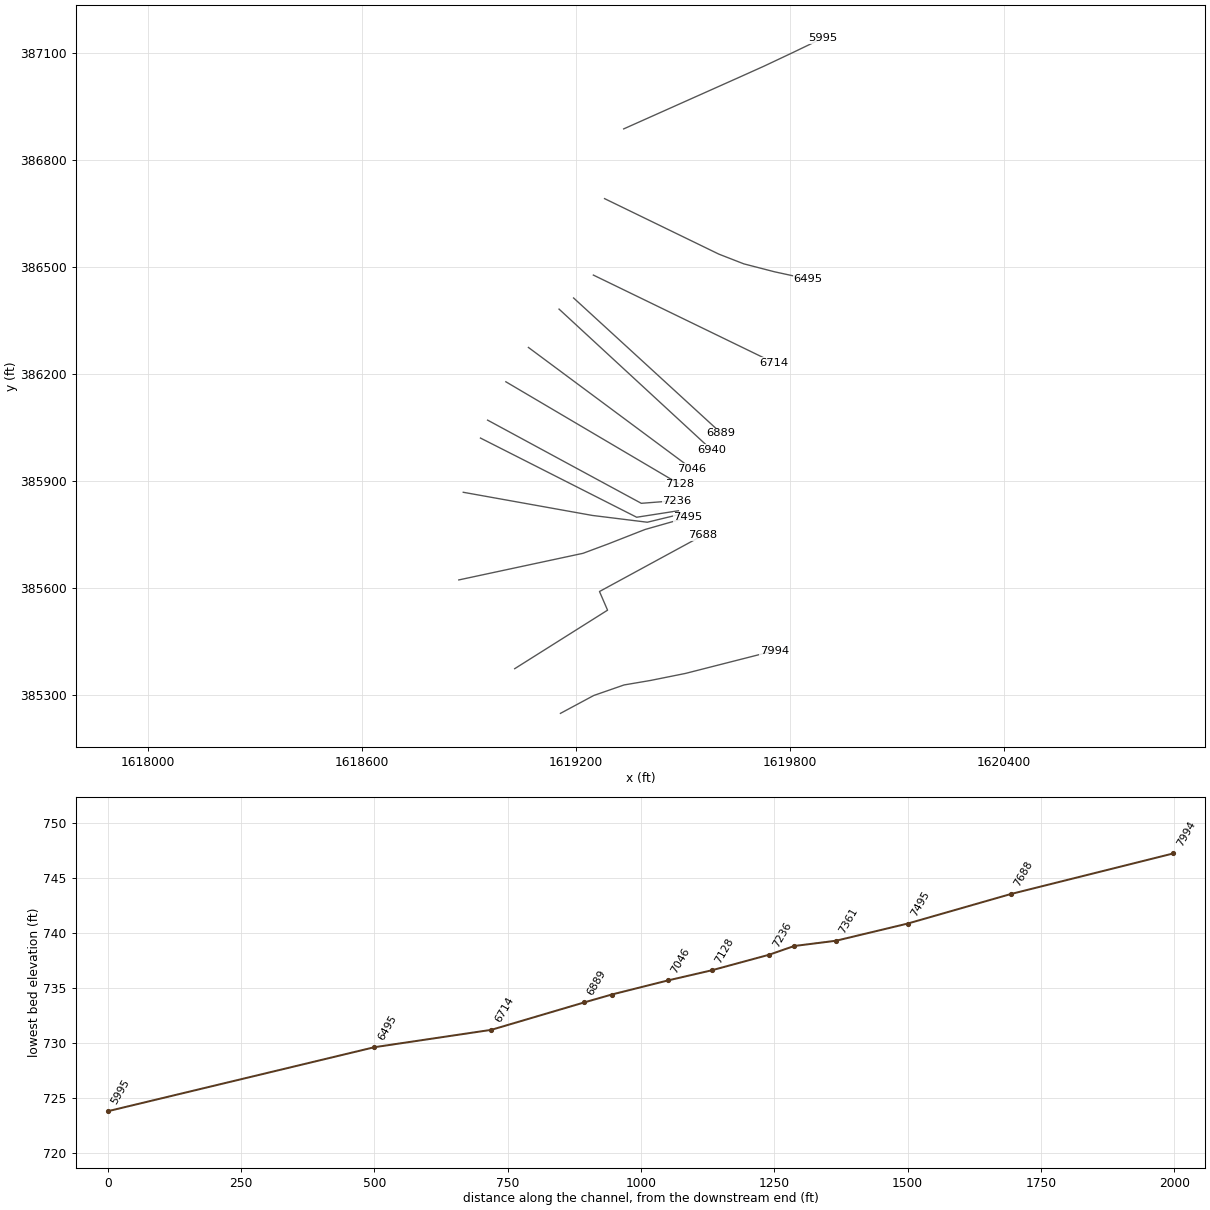
HEC-RAS study BRUSHRN.prj: BRUSHRN

--- BRUSHRN.g01 (geometry) --- (continued)

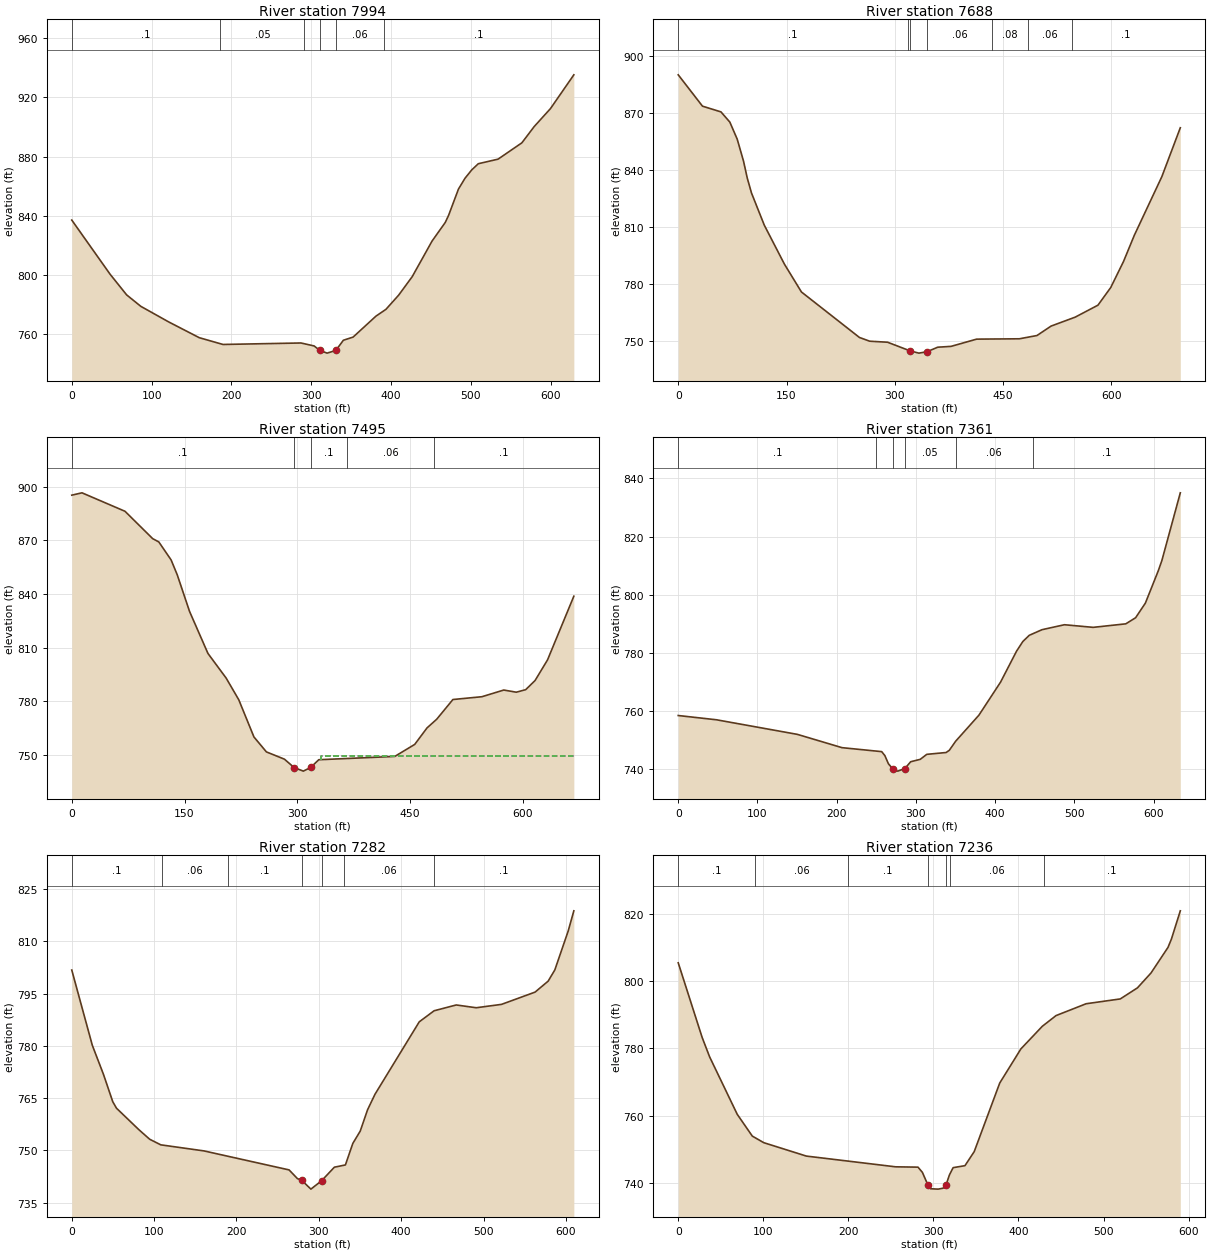
Type RM Length L Ch R = 1 ,7994    ,286.3,305.5,324
BEGIN DESCRIPTION:
Structure 10 XS 1
END DESCRIPTION:
XS GIS Cut Line= 6
1619155.96267159385247.6317057611619249.51858684385297.863232583
1619334.53219634385327.3848270921619408.45363642385339.938279673
1619506.63782325385359.6898805951619756.21475193385423.296380669
#Sta/Elev= 30
       0  837.12      48  800.56    68.7  786.62    86.5  778.86   121.6  768.29
   159.7   757.7   189.4  753.12   287.1  754.12   303.5  752.13   310.8  749.11
   319.8  747.27   330.8749.0969   340.2  755.96   352.4   758.1   381.1  772.28
   393.5  776.82   409.4  786.38   426.5  798.96   451.3  822.94   467.8  835.48
     472  840.29   484.4  858.09   492.6  865.38   500.9  870.94   509.2  875.17
     534  878.27   563.8  889.29   579.3  900.31   599.6  912.39   628.9  935.21
#Mann= 6 ,-1,0
       0      .1       0  186.19     .05       0  291.16      .1       0
   310.8    .045       0   330.8     .06       0  391.31      .1       0
Bank Sta=310.8,330.8
XS Rating Curve= 0 ,0
Exp/Cntr(USF)=0,0
Exp/Cntr=0.3,0.1

Type RM Length L Ch R = 1 ,7688    ,211,193,171.9
XS GIS Cut Line= 4
1619027.66048508385372.9784121311619288.11200337385537.108698324
1619265.47337639385589.4384480721619556.02022708385747.353529868
#Sta/Elev= 30
       0  890.17    33.6  873.66    59.2  870.65    71.5  865.27    81.7  856.29
    90.4   844.8    95.7   835.7   101.5  827.92   119.2  811.01   147.1  790.46
   170.7  775.78   251.1  751.81   265.3  749.85     290  749.31   321.3744.7554
   333.4  743.57   344.6 744.305   359.5  746.69     378  747.13   413.4  750.94
   472.6  751.12     497  752.84   516.6  757.82     550  762.53   581.5  768.83
   599.2  778.12   616.9  791.83   631.9  805.66     670  836.51   695.6  862.29
#Mann= 7 ,-1,0
       0      .1       0  317.85     .06       0   321.3    .045       0
   344.6     .06       0  434.87     .08       0  484.87     .06       0
  544.87      .1       0
Bank Sta=321.3,344.6
XS Rating Curve= 0 ,0
Exp/Cntr(USF)=0,0
Exp/Cntr=0.3,0.1

Type RM Length L Ch R = 1 ,7495    ,137.8,134.4,129
BEGIN DESCRIPTION:
Structure 9 XS 4
END DESCRIPTION:
XS GIS Cut Line= 6
1618870.84841242385621.9380437581618962.51719233385641.582033336
1619219.19089159385696.5825795081619290.10282326385722.996896759
1619392.99402167385763.3317898361619513.81202151385797.700815588
#Sta/Elev= 30
       0  895.32    13.6  896.63    70.8  886.31   107.7  870.97   115.8  869.16
   132.2  859.06   140.4  850.68   156.7  830.28   181.2  806.74   205.4  792.96
   222.2  780.83   242.4  759.99     259  751.64   282.9  747.59   295.8  742.91
   308.1  740.89  317.97742.9816   328.6  747.27   429.8  749.12   456.3  755.85
   472.7  765.09   485.6  769.95   507.1  780.96   545.7  782.53   574.8  786.27
   591.4  785.06   603.9  786.47   616.4  791.58     633  803.15     668  838.78
#Mann= 5 ,-1,0
       0      .1       0   295.8    .045       0  317.97      .1       0
  366.25     .06       0  481.92      .1       0
#XS Ineff= 2 , 0
                          331.56          749.46
Permanent Ineff=
       F       F
Bank Sta=295.8,317.97
XS Rating Curve= 0 ,0
Exp/Cntr(USF)=0,0
Exp/Cntr=0.3,0.1

Type RM Length L Ch R = 1 ,7361    ,80.4,78.5,73.6
XS GIS Cut Line= 4
1618883.37006027 385867.797071191619245.42640806385802.834807829
1619399.60351311385783.7792105771619507.00778853385809.764115921
#Sta/Elev= 30
       0  758.45    48.2  756.99   150.4  751.97   206.7   747.4   256.8  746.03
   260.8  744.67   265.3  741.85   271.3739.9538   277.1  739.33     286  740.21
   293.4  742.56   305.5  743.39   313.7   745.1   338.1  745.73   342.1  746.48
   350.2  749.63   379.5  758.57   406.8  769.92     427  780.58     435  783.92
   443.1  786.04   459.2  787.97   487.4  789.67   523.7  788.77   564.9  789.98
   577.3  792.08   589.6   797.1     606   808.3   610.4  811.73   633.7  835.03
#Mann= 6 ,-1,0
       0      .1       0     250     .05       0   271.3    .045       0
     286     .05       0     350     .06       0  447.84      .1       0
Bank Sta=271.3,286
XS Rating Curve= 0 ,0
Exp/Cntr(USF)=0,0
Exp/Cntr=0.3,0.1

Type RM Length L Ch R = 1 ,7282    ,46.9,46.7,45.9
BEGIN DESCRIPTION:
Structure 9 XS 3
END DESCRIPTION:
XS GIS Cut Line= 3
1618931.69256484386019.8556422851619369.76840937385797.781550801
1619486.87779355385815.998566118
#Sta/Elev= 30
       0  801.78      25  780.13    38.5  771.82    49.8  763.95    54.3   762.1
    81.2  755.99    94.6  753.18   108.1  751.57   160.5  749.83   263.9  744.37
     274  741.88   279.5  741.33   290.4  738.85   303.4  741.26   318.9  745.15
   332.3   745.8   341.3  751.98   350.3  755.52   359.2  761.64   368.2  766.09
     422  786.91     440  790.08   466.9  791.75   491.1  790.95   521.9  791.92
   562.6  795.44   578.5  798.59   586.6  801.81   602.8  812.96   609.7  818.79
#Mann= 7 ,-1,0
       0      .1       0     110     .06       0     190      .1       0
   279.5    .045       0   303.4      .1       0     330     .06       0
     440      .1       0
Bank Sta=279.5,303.4
XS Rating Curve= 0 ,0
Exp/Cntr(USF)=0,0
Exp/Cntr=0.3,0.1

Type RM Length L Ch R = 1 ,7236    ,108,108,107.2
BEGIN DESCRIPTION:
Structure 9 XS 2
END DESCRIPTION:
XS GIS Cut Line= 3
1618951.64453399386070.1693036371619382.78056316385836.818012194
1619482.54040895385844.625304473
#Sta/Elev= 30
       0  805.51    28.1  783.28    36.9  777.48    69.4  760.35    87.1  753.86
   100.6   751.9   150.6  747.91   255.5  744.71   281.9  744.61   287.1  743.04
   293.7  739.19   296.7  738.17   305.5  738.06   311.4  738.34  314.71739.2287
   318.9  742.32   323.2  744.46   337.1  745.05     348  749.24     378  769.68
   402.9  779.86   428.1   786.6   444.2  789.78   479.6  793.31   519.7  794.74
   539.9  798.04   555.8  802.46   575.8  810.09   579.8  812.55   590.3     821
#Mann= 7 ,-1,0
       0      .1       0      90     .06       0     200      .1       0
   293.7    .045       0  314.71      .1       0     320     .06       0
     430      .1       0
Bank Sta=293.7,314.71
XS Rating Curve= 0 ,0
Exp/Cntr(USF)=0,0
Exp/Cntr=0.3,0.1

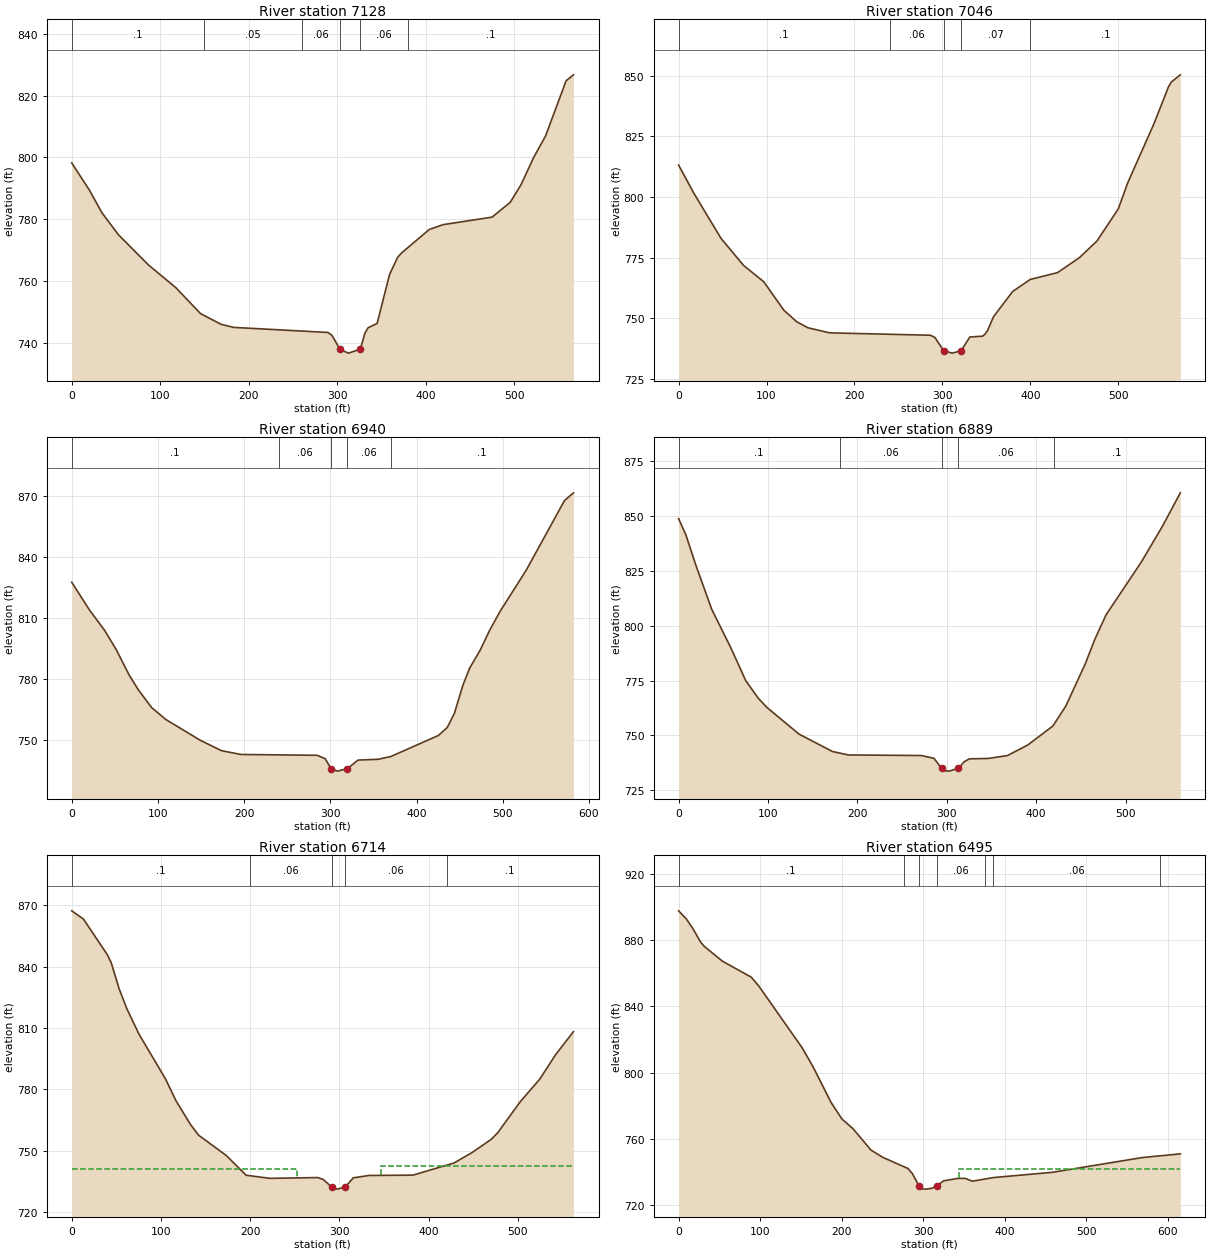
Type RM Length L Ch R = 1 ,7128    ,83.4,82,81.2
BEGIN DESCRIPTION:
Structure 9 XS 1
END DESCRIPTION:
XS GIS Cut Line= 2
1619002.82567226386177.7364416991619491.21517815385889.734104306
#Sta/Elev= 30
       0  798.19    20.1  789.34    33.9  782.17    52.6  775.01    86.5  765.22
   117.6  757.84   145.5  749.44   168.7  745.97   182.9  744.97   289.4  743.33
   293.9  742.45   303.3  737.82   312.6  736.64   325.2  737.82   326.6  738.41
   331.2  743.02   334.8  744.82   345.1  746.25   359.1  762.03   368.3  767.67
     373  769.13     404  776.65   419.7  778.22     475  780.65   495.5  785.44
   507.7  791.13   522.1  800.01   535.5  806.95   558.7  824.81     567  826.71
#Mann= 6 ,-1,0
       0      .1       0     150     .05       0     260     .06       0
   303.3    .045       0   325.2     .06       0     380      .1       0
Bank Sta=303.3,325.2
XS Rating Curve= 0 ,0
Exp/Cntr(USF)=0,0
Exp/Cntr=0.3,0.1

Type RM Length L Ch R = 1 ,7046    ,106.4,105.3,104.4
BEGIN DESCRIPTION:
Structure 8 XS 4
END DESCRIPTION:
XS GIS Cut Line= 2
1619066.15148741386274.026379804 1619524.1793011385933.975427219
#Sta/Elev= 30
       0  813.18    17.4  801.53    48.2     783    73.9  771.83    96.8  765.13
   119.7  753.39     134  748.72   146.9  746.17   171.8  744.07   286.4  743.08
   291.4  742.19   301.4  736.71   311.3  735.72   321.3  736.72   331.2  742.37
   345.6  742.69   348.4   743.5   351.3  745.03   358.1  750.73   379.9  761.12
   399.9  766.07   430.9  768.87   455.8  775.05   475.7  781.88     500  795.14
   510.6  805.76   540.5  830.17   557.1  845.44   560.4  847.39   570.5  850.32
#Mann= 5 ,-1,0
       0      .1       0     240     .06       0   301.4    .045       0
   321.3     .07       0     400      .1       0
Bank Sta=301.4,321.3
XS Rating Curve= 0 ,0
Exp/Cntr(USF)=0,0
Exp/Cntr=0.3,0.1

Type RM Length L Ch R = 1 ,6940    ,51.7,51.8,51.8
BEGIN DESCRIPTION:
Structure 8 XS 3
END DESCRIPTION:
XS GIS Cut Line= 2
1619152.03170248386381.5935178671619579.69782397 385986.89151933
#Sta/Elev= 30
       0  827.62    20.6  813.92    38.2  803.87    51.8  794.25    66.4  782.01
    77.2  774.57    92.6  765.83     109  759.95     149  749.69   173.5  744.56
   196.1  742.66   284.7  742.25     294  740.54   300.9   735.6   308.2  734.44
  319.69735.6598   332.1  739.89   355.4  740.28   370.3  741.68   425.4  752.05
   435.6  755.98   443.9  762.98   453.7  776.81   461.6  785.29   473.4  793.83
   484.9  804.05     497  813.36   527.3  833.67   571.6  867.97     582  871.76
#Mann= 5 ,-1,0
       0      .1       0     240     .06       0   300.9    .045       0
  319.69     .06       0     370      .1       0
Bank Sta=300.9,319.69
XS Rating Curve= 0 ,0
Exp/Cntr(USF)=0,0
Exp/Cntr=0.3,0.1

Type RM Length L Ch R = 1 ,6889    ,171,174.1,175.9
BEGIN DESCRIPTION:
Structure 8 XS 2
END DESCRIPTION:
XS GIS Cut Line= 2
1619192.80311771386412.8226869811619606.58960849386033.735273003
#Sta/Elev= 30
       0  848.78     8.2  841.35    19.5  827.33      37  807.53    58.7   789.7
      75  775.03    89.2  766.88    98.8  762.75   134.7  750.58   172.1  742.66
   189.9  741.09   271.5  740.83   285.7  739.55   294.2  734.95     297  733.95
   302.6  733.72   312.8734.9816   319.6  738.05   325.3  739.32   346.3  739.49
   367.8  740.82   390.4  745.58   418.7   754.3   433.1  763.36   454.8  782.54
   465.6  793.83   478.2  804.97   517.8  829.14   541.6   845.6   561.2  860.54
#Mann= 5 ,-1,0
       0      .1       0     180     .06       0   294.2    .045       0
   312.8     .06       0     420      .1       0
Bank Sta=294.2,312.8
XS Rating Curve= 0 ,0
Exp/Cntr(USF)=0,0
Exp/Cntr=0.3,0.1

Type RM Length L Ch R = 1 ,6714    ,219.4,219.3,217.3
BEGIN DESCRIPTION:
Structure 8 XS 1
END DESCRIPTION:
XS GIS Cut Line= 2
1619248.32164059386477.0159790511619754.06068486386231.520010731
#Sta/Elev= 30
       0  867.31    13.1   863.3    39.8  845.89    44.2  841.98    53.1  829.18
      62  819.21    75.4  806.96     105  785.16   116.9  774.35   133.2  762.76
   142.1  757.61   173.2  747.66   195.4  738.02   222.1   736.5   275.4  736.88
   281.6  736.03  291.08732.3508   297.7  731.23   306.6  732.34   315.5  736.75
   333.2  737.92   382.2  738.06   428.3  743.99   448.9   749.2   470.2  755.64
   477.4  758.84   502.2  773.77   524.4     785   542.2  796.99   562.2  808.24
#Mann= 5 ,-1,0
       0      .1       0     200     .06       0  291.08    .045       0
   306.6     .06       0     420      .1       0
#XS Ineff= 2 , 0
          252.19  740.96  346.27          742.31
Permanent Ineff=
       F       F
Bank Sta=291.08,306.6
XS Rating Curve= 0 ,0
Exp/Cntr(USF)=0,0
Exp/Cntr=0.3,0.1

Type RM Length L Ch R = 1 ,6495    ,490,500,508.7
XS GIS Cut Line= 6
1619279.72325084386691.4769151661619442.75999826386612.289737582
1619600.17438158386535.8322133421619670.27037001 386508.50648059
1619756.15143184386486.3057375851619849.49770184386466.012799174
#Sta/Elev= 30
       0   897.6     9.3  892.83    17.5  886.91    27.1  878.67    31.6  876.12
    53.8  867.22    89.1  857.59    98.3  852.31   151.6  814.96     165   803.5
   187.2  781.88   200.5  771.92   213.9  766.19   236.1  753.22   250.9  748.75
   281.4  742.13   286.8  739.07  294.89731.6935   298.4   729.8   302.8  729.65
   310.8   730.1   316.8  731.62   325.1  734.64   342.8  736.13   351.7  736.14
   360.5  734.44   386.2  736.62   459.2  739.83   569.3  748.73   615.7  750.92
#Mann= 7 ,-1,0
       0      .1       0  276.25     .06       0  294.89    .045       0
   316.8     .06       0  376.25     .05       0  386.25     .06       0
  590.19      .1       0
#XS Ineff= 2 , 0
                           343.7          741.55
Permanent Ineff=
       F       F
Bank Sta=294.89,316.8
XS Rating Curve= 0 ,0
Exp/Cntr(USF)=0,0
Exp/Cntr=0.3,0.1

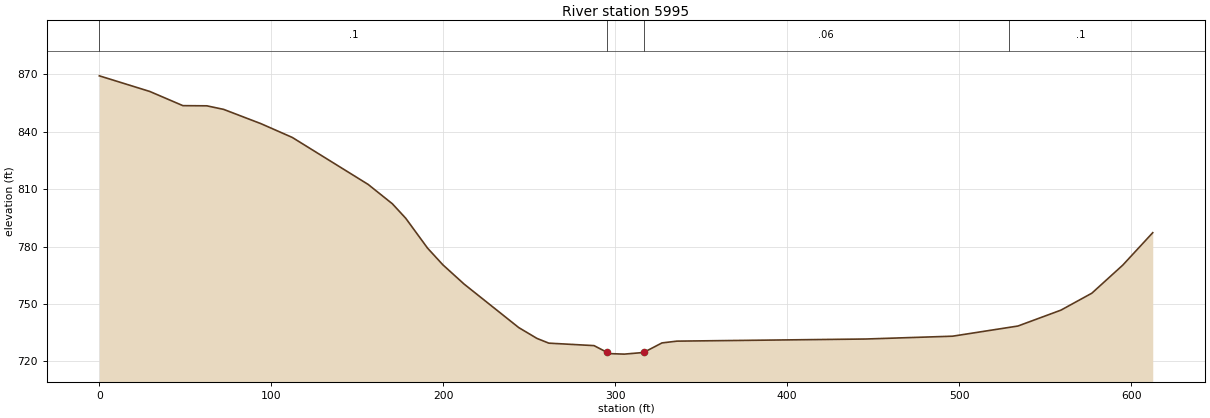
Type RM Length L Ch R = 1 ,5995    ,316.6,301.4,285.1
XS GIS Cut Line= 6
1619333.39669992386887.0585450081619498.89210384386960.969814509
1619658.68082626387032.3318765011619727.08620125387063.084439665
1619806.23827392387100.4275408391619890.76369542387141.066239089
#Sta/Elev= 30
       0  869.12    29.3  860.97    48.6  853.55    62.5  853.46    72.3   851.6
      94  844.14   112.2  836.96   156.3  812.44   170.4  802.33   178.2  794.74
   190.9  779.14   199.8  770.44   212.1  760.42   243.9  737.69   254.5  732.03
   261.4  729.56   287.7  728.27   295.4  724.68   296.9  724.09   305.3  723.83
  316.53724.6931   327.2  729.68   335.9  730.61   445.7  731.72   496.2  733.19
   534.2   738.5   559.2  746.79   577.2  755.65   595.2  770.32   612.6  787.23
#Mann= 4 ,-1,0
       0      .1       0   295.4    .045       0  316.53     .06       0
  528.77      .1       0
Bank Sta=295.4,316.53
XS Rating Curve= 0 ,0
Exp/Cntr(USF)=0,0
Exp/Cntr=0.3,0.1