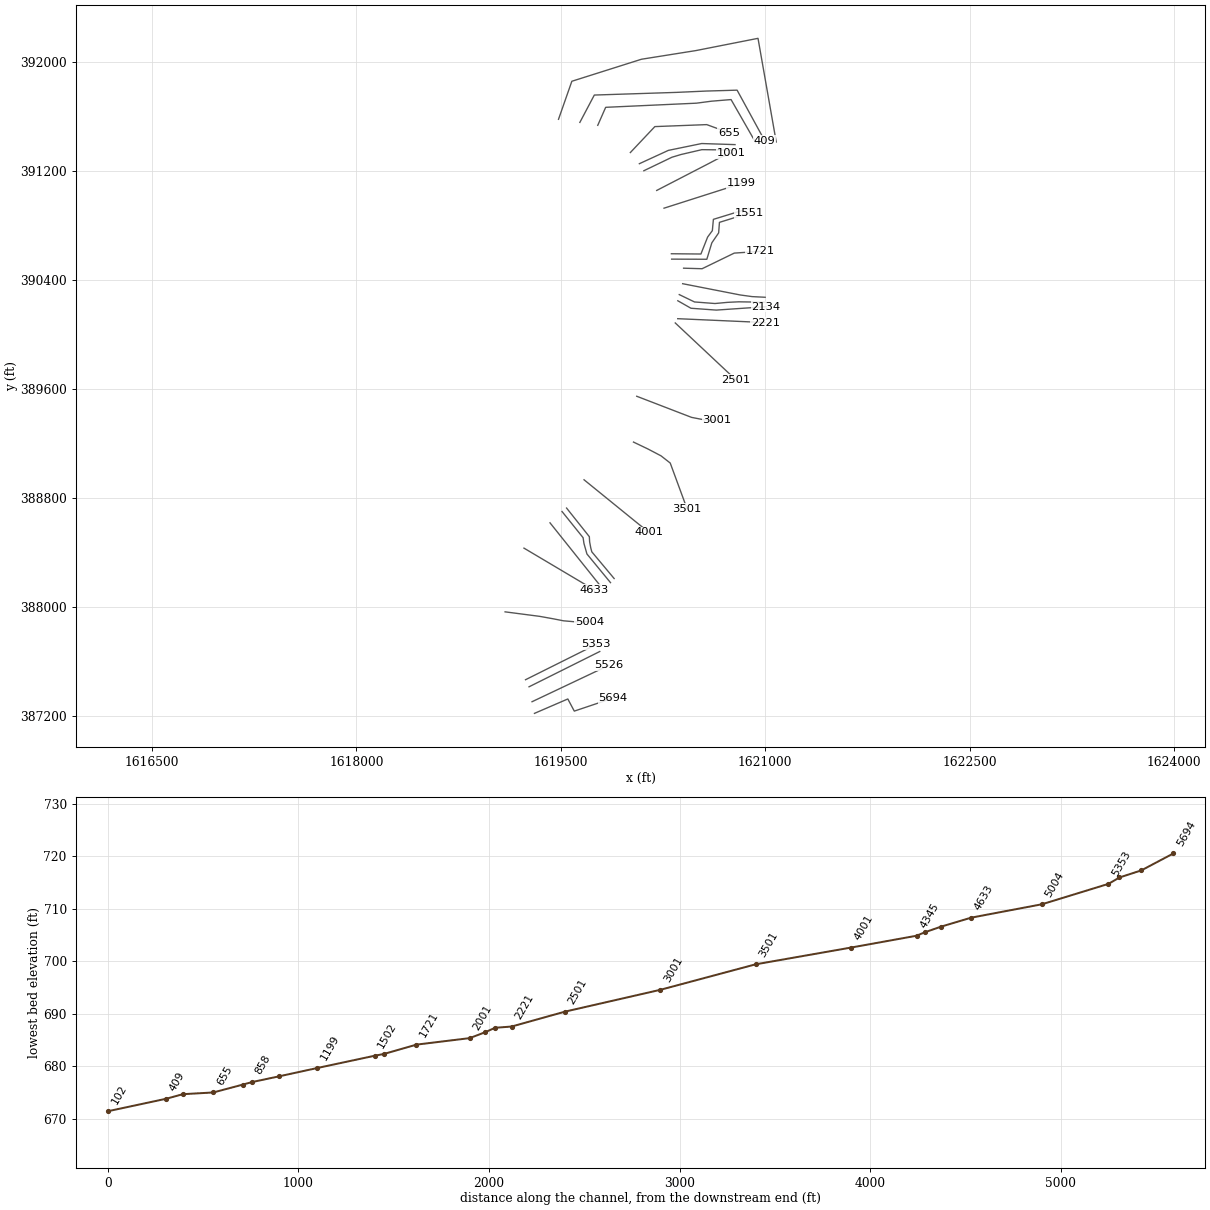
HEC-RAS study BRUSHRN.prj: BRUSHRN

--- BRUSHRN.g01 (geometry) --- (continued)

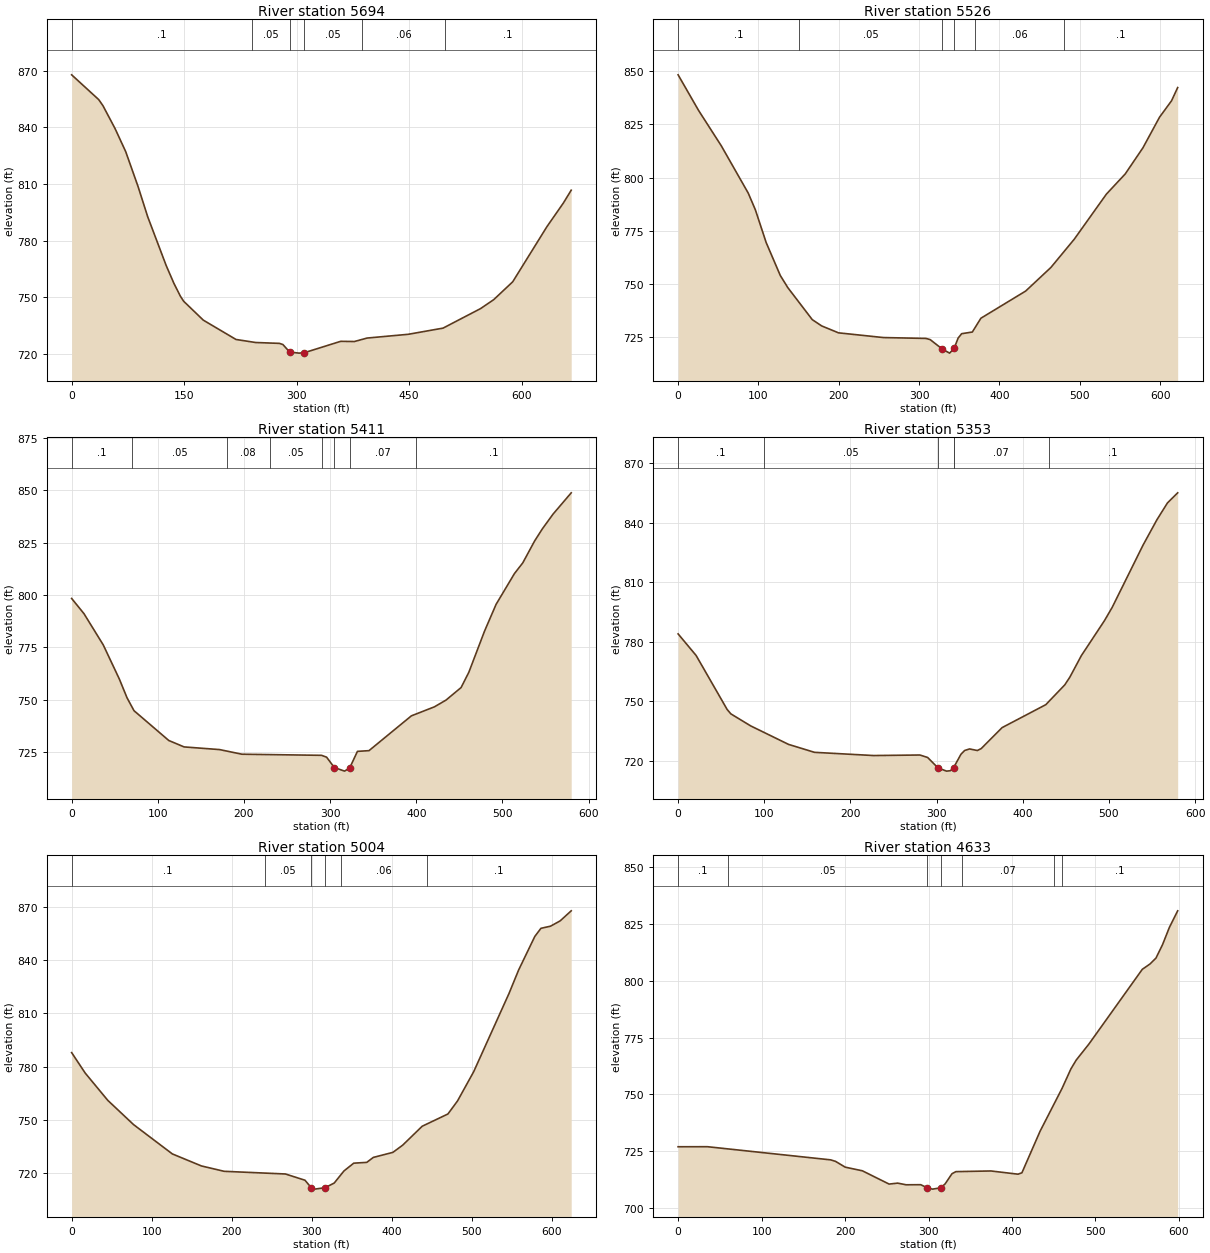
Type RM Length L Ch R = 1 ,5694    ,152.4,168.1,183.8
XS GIS Cut Line= 4
1619306.99732642387215.961091093 1619551.7568372387321.706704976
 1619599.2829558387232.5952326021619882.06336147387327.647469801
#Sta/Elev= 30
       0  867.78    36.1  854.67    41.8  851.41    57.9  839.33    72.1  827.11
    88.4  808.85   101.4  792.69     126  766.91   136.3  757.48     145  750.63
   149.4  747.96   175.5     738   219.1  727.77   245.2  726.17     277  725.71
   281.6   725.1   290.6  721.12   303.2  720.55   309.9  720.74   358.6  726.79
   376.9  726.69   393.8  728.52   448.7  730.51   495.1  733.78   545.1  744.11
   562.6  748.84   587.9  758.27   633.5  787.43   655.5  799.99   665.9  806.74
#Mann= 6 ,-1,0
       0      .1       0     240     .05       0   290.6    .045       0
   309.9     .05       0  387.62     .06       0  497.62      .1       0
Bank Sta=290.6,309.9
XS Rating Curve= 0 ,0
Exp/Cntr(USF)=0,0
Exp/Cntr=0.3,0.1

Type RM Length L Ch R = 1 ,5526    ,114.9,115,115.1
XS GIS Cut Line= 2
1619289.17503194387301.5081045721619851.17138438387567.654368729
#Sta/Elev= 30
       0  848.38    25.4  831.66    53.8  814.92    87.3  792.67    96.2  784.78
   109.6   769.4   127.2  753.87   136.6  748.14     167  733.09   178.7  730.13
   199.7  726.87   255.5  724.65   308.6  724.24   313.8  723.67   328.9  719.21
   337.9  717.32   343.5   719.5   348.5  724.39   352.9  726.47   366.2  727.25
   376.9  733.76   432.6  746.55     464  757.66   493.1  770.98   533.1  792.21
   556.5  801.69   578.6  814.04   599.2  828.41   614.2  836.18   621.8  842.38
#Mann= 6 ,-1,0
       0      .1       0     150     .05       0   328.9    .045       0
   343.5     .05       0     370     .06       0     480      .1       0
Bank Sta=328.9,343.5
XS Rating Curve= 0 ,0
Exp/Cntr(USF)=0,0
Exp/Cntr=0.3,0.1

Type RM Length L Ch R = 1 ,5411    ,58.1,58.1,58.1
BEGIN DESCRIPTION:
Structure 7 XS 3
END DESCRIPTION:
XS GIS Cut Line= 2
1619267.31675262387411.0579942471619786.08671403387669.950191424
#Sta/Elev= 30
       0  798.35    14.3  791.11    36.7  776.18    55.4  759.87    64.3  750.94
    72.4  744.79   112.7  730.59   130.5  727.51   171.7  726.24   197.6  724.03
     290   723.5   295.9  722.62   304.9  717.66   316.8  715.96   322.8  717.55
   331.7  725.39   345.1  725.73   394.3  742.34   421.1  746.65   434.5  749.86
     452  755.84     461  763.14   479.2  782.75   492.6  795.53   513.9  810.21
   523.6  815.34   537.3  825.75   546.3  831.56   558.7  838.58   579.8  848.76
#Mann= 8 ,-1,0
       0      .1       0      70     .05       0     180     .08       0
     230     .05       0     290     .07       0   304.9    .045       0
   322.8     .07       0     400      .1       0
Bank Sta=304.9,322.8
XS Rating Curve= 0 ,0
Exp/Cntr(USF)=0,0
Exp/Cntr=0.3,0.1

Type RM Length L Ch R = 1 ,5353    ,353.5,349,342.3
BEGIN DESCRIPTION:
Structure 7 XS 2
END DESCRIPTION:
XS GIS Cut Line= 2
 1619241.3733083387462.8986813081619760.14326972387721.790878485
#Sta/Elev= 30
       0  783.96    20.9  773.08    56.9  745.85    61.2  743.63    84.3  737.54
   128.2  728.22   158.3  724.22   226.9   722.6   280.6  722.87   289.6  721.63
   301.5  716.43   311.5  714.74     316  714.95  319.64716.4053   328.3  723.27
   332.6  725.16   338.3  725.93   347.3  725.14   351.8  726.12     376  736.68
   426.7  748.25   448.7  758.21   454.6  762.09     468  772.99   494.8  790.62
   503.8  797.34   539.5  828.65   555.7  841.53     568  850.06   579.8  855.12
#Mann= 6 ,-1,0
       0      .1       0     100     .05       0   301.5    .045       0
  319.64     .05       0     320     .07       0     430      .1       0
Bank Sta=301.5,319.64
XS Rating Curve= 0 ,0
Exp/Cntr(USF)=0,0
Exp/Cntr=0.3,0.1

Type RM Length L Ch R = 1 ,5004    ,374.6,371,368.9
BEGIN DESCRIPTION:
Structure 7 XS 1
END DESCRIPTION:
XS GIS Cut Line= 6
1619091.36962493387961.0947827551619345.51773867387927.956069499
 1619444.6231835387910.0981655871619519.58596009387895.422013834
1619610.07987359387887.4479484261619709.89397842387890.112969339
#Sta/Elev= 30
       0  787.85    16.9  776.34    45.1  760.95    77.4  747.23   125.8  730.71
   162.1  723.93   190.5   720.9   267.1  719.39   291.5  715.87  299.26711.7159
   303.6  710.85   316.6  711.65     328  714.27   340.2   721.1   352.4  725.49
   368.7  725.94   376.9  728.74   401.3  731.58   413.5  735.62   437.9  746.31
   470.1  753.24   482.1  760.61   502.2  777.02   546.3  821.11   558.3  834.33
   578.6  853.35   586.3  857.96   598.3  859.18   610.3  862.16   624.1  867.83
#Mann= 6 ,-1,0
       0      .1       0  241.29     .05       0  299.26    .045       0
   316.6     .05       0   336.3     .06       0  443.39      .1       0
Bank Sta=299.26,316.6
XS Rating Curve= 0 ,0
Exp/Cntr(USF)=0,0
Exp/Cntr=0.3,0.1

Type RM Length L Ch R = 1 ,4633    ,161.4,157,155.6
BEGIN DESCRIPTION:
Structure 6 XS 4
END DESCRIPTION:
XS GIS Cut Line= 2
1619229.95275928388428.7646840421619744.55762946388123.265449015
#Sta/Elev= 30
       0  726.96    35.1  726.98   182.7  721.19   188.6  720.53   200.2  717.97
   220.7  716.38   252.8  710.52     263  710.94   273.2  710.21   290.7  710.25
   298.2  708.93   304.9   708.3  314.81708.8943   319.9  710.61   328.1  715.08
   332.8     716   374.7   716.3   407.2  714.88   411.9   715.5   433.7  733.83
     460  752.68   470.6  761.25     477  765.16   492.1  772.16   556.1  805.09
   565.4  807.47   572.5  810.05   580.3  815.91   588.6  823.58   598.5  830.86
#Mann= 7 ,-1,0
       0      .1       0      60     .05       0   298.2    .045       0
  314.81     .05       0     340     .07       0     450     .06       0
     460      .1       0
Bank Sta=298.2,314.81
XS Rating Curve= 0 ,0
Exp/Cntr(USF)=0,0
Exp/Cntr=0.3,0.1

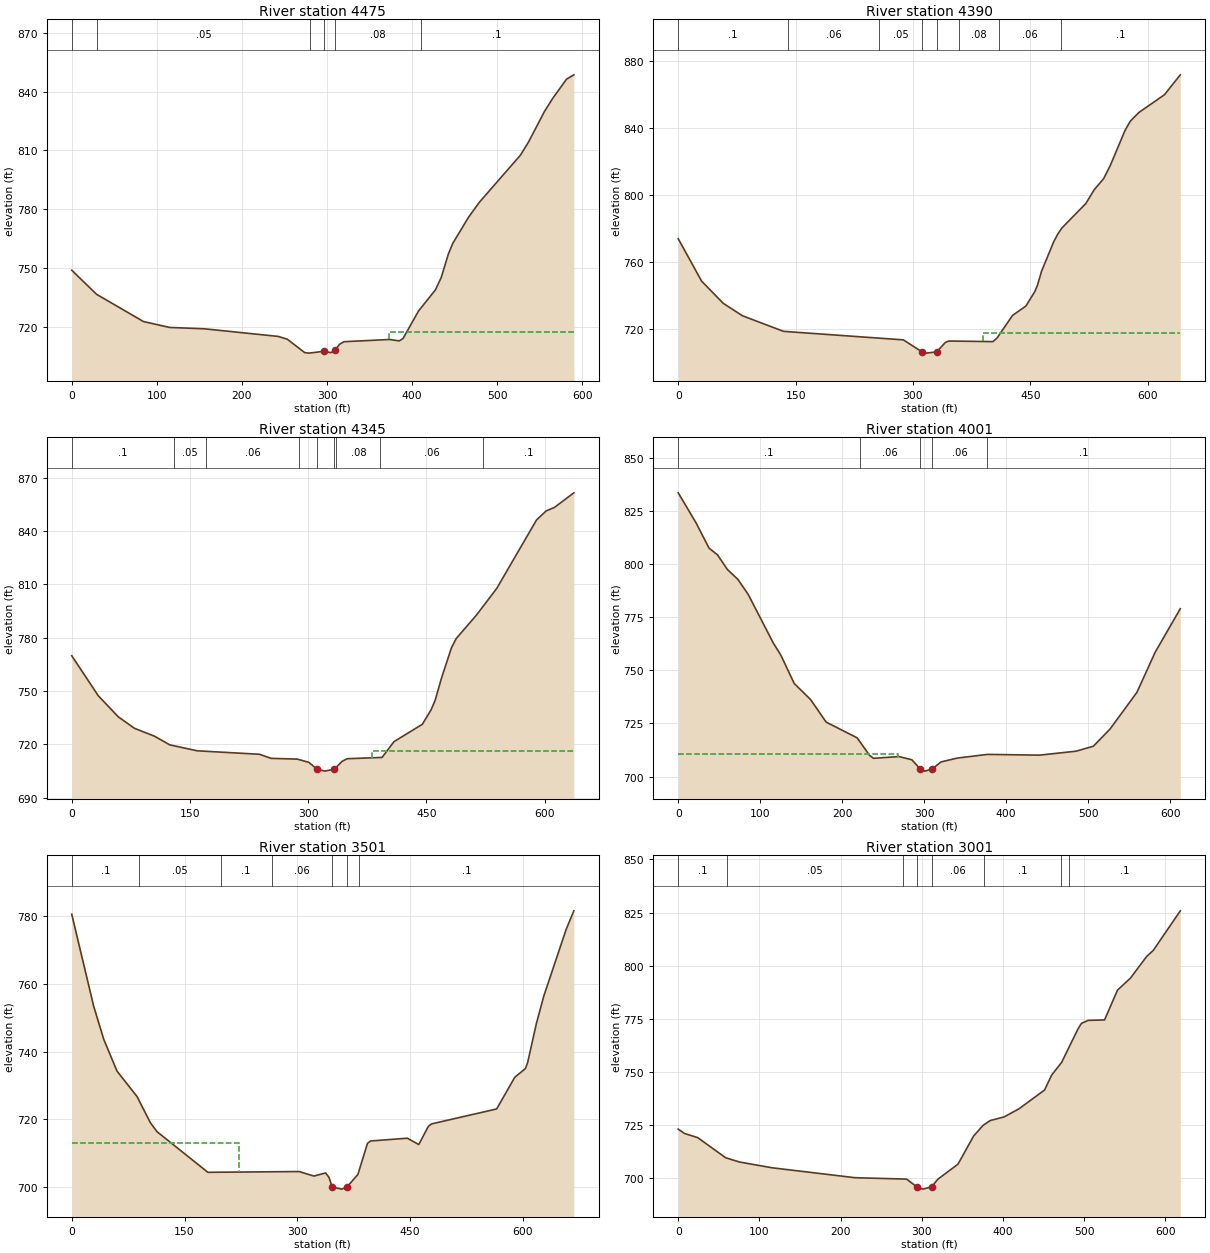
Type RM Length L Ch R = 1 ,4475    ,91.6,85.1,84.4
XS GIS Cut Line= 2
1619421.06001106388614.417130882 1619789.3874302388153.413780467
#Sta/Elev= 30
       0  748.88    29.1  736.61    84.3   722.7     115   719.7     156     719
   242.6  715.12   253.3   713.7   273.8  706.86   278.9   706.6   296.7  707.57
   304.5  706.84   309.6   708.2   314.7  711.09   319.8  712.42   373.5  713.56
   384.9  712.83   389.4  714.09   407.6  728.12   427.4  738.84   434.2  745.13
   442.7  757.25   447.8  762.56   466.3  775.87   479.1  783.56   527.4  807.59
   536.8  814.22   555.6  829.86   565.6  836.73   581.6  846.35   590.1  848.52
#Mann= 6 ,-1,0
       0      .1       0      30     .05       0     280     .08       0
   296.7    .045       0   309.6     .08       0     410      .1       0
#XS Ineff= 2 , 0
                          373.26          717.58
Permanent Ineff=
       F       F
Bank Sta=296.7,309.6
XS Rating Curve= 0 ,0
Exp/Cntr(USF)=0,0
Exp/Cntr=0.3,0.1

Type RM Length L Ch R = 1 ,4390    ,46.4,45,43.4
BEGIN DESCRIPTION:
Structure 6 XS 3
END DESCRIPTION:
XS GIS Cut Line= 5
 1619509.3558642388697.3963249371619663.94025132 388505.33693488
1619670.18608514388463.1775565741619692.04650352388385.885363015
1619864.99676928388175.541487214
#Sta/Elev= 30
       0  773.87    29.9  748.53    57.6  735.25    82.2  727.82   134.6  718.54
   287.8  713.45  311.66  706.27   316.8  705.53  330.33  706.27   341.5  711.94
   345.9  712.76   402.3   712.4   407.5  714.54   427.3  728.03   444.4  733.66
   455.7   742.2   459.3  746.21   464.4  754.43     480  772.09   485.2  776.67
   490.3  780.21   521.1  794.95   531.8  803.18   543.8  809.76   552.4  817.74
   571.1  838.53   577.9  844.11   588.7  849.23   621.5  859.88   641.8  871.78
#Mann= 8 ,-1,0
       0      .1       0     140     .06       0  256.54     .05       0
  311.66    .045       0  330.33     .05       0  359.16     .08       0
  409.49     .06       0  489.49      .1       0
#XS Ineff= 2 , 0
                          390.04          717.49
Permanent Ineff=
       F       F
Bank Sta=311.66,330.33
XS Rating Curve= 0 ,0
Exp/Cntr(USF)=0,0
Exp/Cntr=0.8,0.6

Type RM Length L Ch R = 1 ,4345    ,332.5,344.4,347.7
BEGIN DESCRIPTION:
Structure 6 XS 2
END DESCRIPTION:
XS GIS Cut Line= 6
1619542.63806202388722.8016181381619709.70769103388512.893622715
1619711.84960935388475.4100521041619720.41728264 388429.35880821
1619727.91399676388401.5138700411619891.77074829388205.528343703
#Sta/Elev= 30
       0  769.75    33.6  747.28    59.1  735.36    79.6  728.93   105.1  724.47
   124.4  719.61   159.2  716.28   238.1  714.33   252.9  712.04   286.1  711.61
   300.7   709.8  311.24705.9656     321  704.85   333.2  705.96   342.8  710.31
   349.4  711.83   393.7  712.56   408.8  721.44   444.8  731.21   455.8  739.27
     461  744.64   469.1  757.19   481.7  774.21   487.8  779.46   513.1  792.45
   539.2  807.65   589.6  846.09   601.8  851.21   612.4   853.2     637  861.41
#Mann= 9 ,-1,0
       0      .1       0     130     .05       0     170     .06       0
  288.28     .05       0  311.24    .045       0   333.2     .05       0
  335.82     .08       0   391.5     .06       0   521.5      .1       0
#XS Ineff= 2 , 0
                          381.49          716.23
Permanent Ineff=
       F       F
Bank Sta=311.24,333.2
XS Rating Curve= 0 ,0
Exp/Cntr(USF)=0,0
Exp/Cntr=0.3,0.1

Type RM Length L Ch R = 1 ,4001    ,506.5,500,497.7
BEGIN DESCRIPTION:
Structure 6 XS 1
END DESCRIPTION:
XS GIS Cut Line= 6
1619670.89208792 388930.331033261619811.60473301  388816.0881515
1619869.83066642 388768.814952091619947.46535367388705.784566343
1620073.62126935388603.3595743331620147.49776201388545.615595341
#Sta/Elev= 30
       0  833.46      22  819.16    37.6  807.44    47.9   804.3      60   797.4
    72.7   792.8    85.3  785.72   115.9  762.88   125.2  757.11   141.5   743.8
   161.5  736.22   180.5  725.62   218.3  718.24   233.4  710.01   238.2  708.61
   269.4  709.44     285  707.92     295  703.69   301.1  702.59   310.1703.6743
   320.6  706.92   340.5  708.73   377.3  710.46   440.7   710.1   485.6  711.98
   506.5  714.32     527  722.49   559.6  739.66   581.8  758.47   612.5  778.97
#Mann= 5 ,-1,0
       0      .1       0  221.25     .06       0     295    .045       0
   310.1     .06       0  376.25      .1       0
#XS Ineff= 2 , 0
          268.57  710.65
Permanent Ineff=
       F       F
Bank Sta=295,310.1
XS Rating Curve= 0 ,0
Exp/Cntr(USF)=0,0
Exp/Cntr=0.3,0.1

Type RM Length L Ch R = 1 ,3501    ,484,500,502.2
XS GIS Cut Line= 6
1620033.83197884389207.1290360841620140.24285525389156.156697094
1620235.74135192389106.1144743411620303.39410375389053.218254671
1620394.00809576388806.8542460951620426.37089193388718.867217332
#Sta/Elev= 30
       0  780.51    29.1  753.42    42.6  743.58    60.2  734.23    86.8  726.74
   104.5  719.03   113.4  716.36   181.1  704.36   302.4  704.59   322.1  703.26
   337.7  704.17   342.2  702.87   346.5  700.02   359.3   699.4  366.01700.0286
   380.6  703.71   393.4  712.92   397.6  713.61   446.4  714.43   461.6  712.56
   474.4  717.94   478.6  718.65   565.2  723.06   589.4  732.43   603.5  734.99
   606.5  736.82   618.1  748.29   627.8  756.29   657.6  776.01   667.9  781.54
#Mann= 7 ,-1,0
       0      .1       0      90     .05       0  197.99      .1       0
   265.8     .06       0   346.5    .045       0  366.01     .06       0
  381.68      .1       0
#XS Ineff= 2 , 0
          222.69  713.13
Permanent Ineff=
       F       F
Bank Sta=346.5,366.01
XS Rating Curve= 0 ,0
Exp/Cntr(USF)=0,0
Exp/Cntr=0.3,0.1

Type RM Length L Ch R = 1 ,3001    ,504.1,500.1,496.8
XS GIS Cut Line= 6
1620057.60096018389543.3314476761620145.08536525389509.633680418
1620226.73743293389478.1826278421620460.02961725389388.322571337
1620547.26927218389371.3773952571620645.27563784389366.413494423
#Sta/Elev= 30
       0  722.81     7.8  720.79    24.1  718.81    58.4  709.34    75.6  707.31
   115.5  704.61   217.6  699.93   281.3  699.26   293.5695.6808   301.2  694.54
  312.07695.6437   319.7  699.22   344.5  706.31   363.9  719.66   375.4   724.6
   384.2  726.88   401.3   728.6   419.5  732.38   451.1  741.28   459.9  748.35
   472.1  754.28   492.3  770.08   496.5  772.69   504.7  774.12     525  774.34
     541  788.41     557  794.11     577  804.34     585  807.12   618.3  825.79
#Mann= 8 ,-1,0
       0      .1       0      60     .05       0  276.25     .06       0
   293.5    .045       0  312.07     .06       0  376.25      .1       0
  471.25     .06       0  481.25      .1       0
Bank Sta=293.5,312.07
XS Rating Curve= 0 ,0
Exp/Cntr(USF)=0,0
Exp/Cntr=0.3,0.1

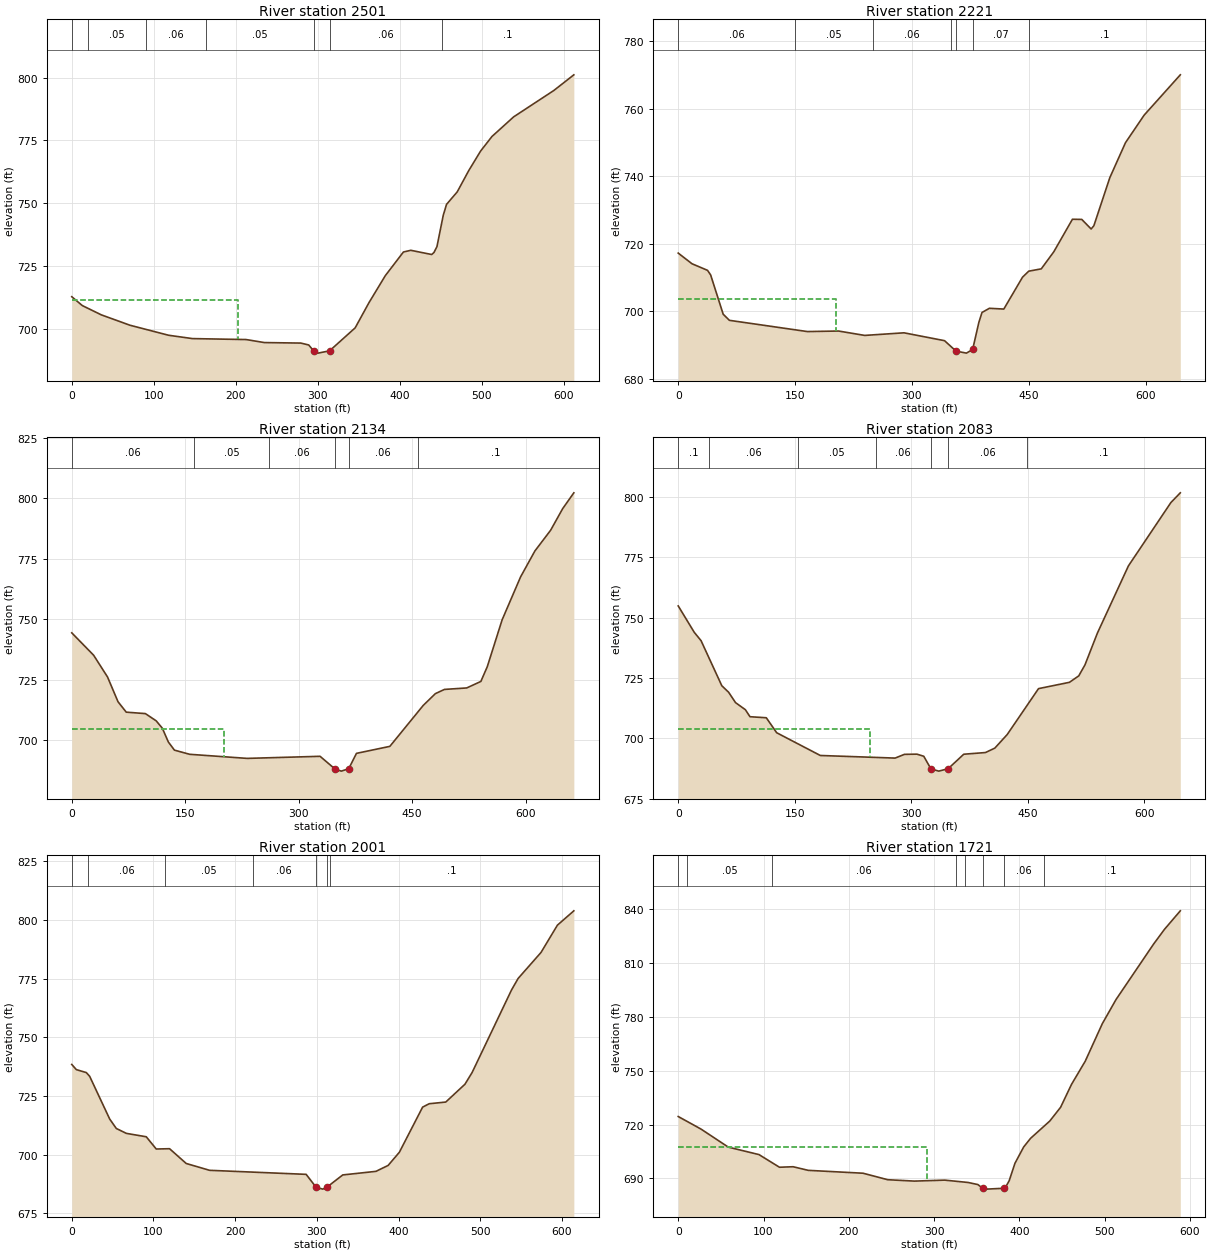
Type RM Length L Ch R = 1 ,2501    ,272.6,280,285.5
BEGIN DESCRIPTION:
Structure 5 XS 4
END DESCRIPTION:
XS GIS Cut Line= 6
1620340.31266509 390081.332668261620408.68785642390017.192704678
1620472.50465792389957.3289792541620600.13826093  389837.6018565
1620718.65541235389726.4262258411620787.31702043389662.592035919
#Sta/Elev= 30
       0  712.82    12.9  709.29    36.2  705.59      71  701.48   118.1  697.49
   147.3  696.16   212.7  695.78     235  694.58   279.4  694.38   289.1  693.62
  295.01691.2737   300.4  690.38   314.5  691.29   345.7  700.42   362.6  710.47
   382.5   721.2   404.6  730.62   413.6  731.29   439.1  729.62   441.9  730.45
   445.5  732.76   453.2  745.24   457.2  749.57   470.2  754.52   484.3  763.01
   498.8   770.8   512.6  776.57   539.1  784.39   588.1  794.88   612.5  801.11
#Mann= 7 ,-1,0
       0     .06       0      20     .05       0      90     .06       0
  163.75     .05       0  295.01    .045       0   314.5     .06       0
  451.25      .1       0
#XS Ineff= 2 , 0
          202.89  711.55
Permanent Ineff=
       F       F
Bank Sta=295.01,314.5
XS Rating Curve= 0 ,0
Exp/Cntr(USF)=0,0
Exp/Cntr=0.3,0.1

Type RM Length L Ch R = 1 ,2221    ,85.7,87,87.7
XS GIS Cut Line= 2
1620358.51270043 390112.678019731621002.49160745 390084.16234857
#Sta/Elev= 30
       0  717.19    17.6  714.04    37.6  712.08    41.6  710.73    57.7  699.08
    65.7  697.26   165.8  693.93   205.8  694.09   239.4  692.79   289.9  693.56
   341.9  691.23   356.6688.1474     370  687.54     378  688.63     386  696.69
     390  699.59   399.5  700.83     418   700.6     442  710.04     450  711.83
   466.1  712.52   482.1  717.55   506.1  727.22   518.1  727.17   530.1  724.34
   533.6  725.29   554.1  739.55   574.2  749.91   598.2  758.09   644.6  770.03
#Mann= 7 ,-1,0
       0     .06       0     150     .05       0     250     .06       0
     350     .07       0   356.6    .045       0     378     .07       0
     450      .1       0
#XS Ineff= 2 , 0
          202.68   703.6
Permanent Ineff=
       F       F
Bank Sta=356.6,378
XS Rating Curve= 0 ,0
Exp/Cntr(USF)=0,0
Exp/Cntr=0.3,0.1

Type RM Length L Ch R = 1 ,2134    ,50.4,51,50.6
BEGIN DESCRIPTION:
Structure 5 XS 3
END DESCRIPTION:
XS GIS Cut Line= 4
1620359.03582034390244.2056015521620455.42214477390189.265396628
1620641.44775092390175.771311208 1621006.7519205390200.831755559
#Sta/Elev= 30
       0   744.4    28.9  735.16    47.3  726.16    61.1  715.97      72  711.65
    97.3  711.05   111.6  708.06   119.7  705.02   127.7  699.31   135.7  695.97
   155.8  694.25   231.9  692.56   328.2  693.42   348.2   688.1   356.3   687.3
  366.03688.2877   376.3  694.64   420.4  697.52   464.5  714.42   480.6   719.3
   492.6  721.04     522  721.65   540.7  724.33   549.2  730.43   568.8  749.77
   593.3  767.56   612.1   778.2   632.9  786.76   648.9  795.72   663.6  802.22
#Mann= 6 ,-1,0
       0     .06       0  160.94     .05       0  260.94     .06       0
   348.2    .045       0  366.03     .06       0  457.46      .1       0
#XS Ineff= 2 , 0
          201.54  704.65
Permanent Ineff=
       F       F
Bank Sta=348.2,366.03
XS Rating Curve= 0 ,0
Exp/Cntr(USF)=0,0
Exp/Cntr=0.3,0.1

Type RM Length L Ch R = 1 ,2083    ,84,82,79.1
BEGIN DESCRIPTION:
Structure 5 XS 2
END DESCRIPTION:
XS GIS Cut Line= 6
1620369.63831603390289.5071740341620481.44645237390235.530832354
1620631.80911848390223.9644734221620725.30385317390232.639242621
1620806.26836569390236.4946955981621002.89646753390233.603105865
#Sta/Elev= 30
       0  754.91    20.6  743.99    29.4  740.52    56.1  721.86    64.9  719.14
    73.8  714.85    86.5  711.91    92.4  709.01   113.4  708.58   126.8  702.37
     183  692.95   279.3  691.87   291.3  693.42   307.4   693.5   316.2  692.63
  325.43687.4035   335.5  686.47   347.6  687.47   367.7  693.47   395.7  694.17
   407.7     696   423.7  701.64     464  720.65   503.8  723.26   515.8  725.93
   523.8  730.48   539.8  743.63   579.8  771.51   634.5  797.75   646.6  801.77
#Mann= 7 ,-1,0
       0      .1       0      40     .06       0  154.16     .05       0
  254.16     .06       0  325.43    .045       0   347.6     .06       0
  448.86      .1       0
#XS Ineff= 2 , 0
          246.98  703.86
Permanent Ineff=
       F       F
Bank Sta=325.43,347.6
XS Rating Curve= 0 ,0
Exp/Cntr(USF)=0,0
Exp/Cntr=0.3,0.1

Type RM Length L Ch R = 1 ,2001    ,271.7,279.4,288.1
BEGIN DESCRIPTION:
Structure 5 XS 1
END DESCRIPTION:
XS GIS Cut Line= 6
1620394.60225467390369.4505303351620646.08370709390320.245248169
1620744.22261843390301.043186843   1620817.82713   390286.642297
1620904.64913484390274.6964547491621000.19848442390269.872973591
#Sta/Elev= 30
       0   738.4     5.6  736.21    17.8  734.95    21.9  733.37    46.4  715.19
    54.5  711.16    66.8  709.07    91.2  707.62   103.4  702.41   119.7  702.54
   140.1  696.25   168.7  693.34   286.9  691.62   299.1  686.13   307.2  685.33
   312.3  686.15   331.7  691.37   372.4   692.9   387.3  695.43     401  701.02
   429.5  720.25   437.6  721.69   457.8   722.4   481.3  729.99   490.1     735
   538.4  770.18   546.4  775.03   574.4  786.09   594.5  797.72   614.6  803.82
#Mann= 7 ,-1,0
       0      .1       0      20     .06       0  113.75     .05       0
  221.25     .06       0   299.1    .045       0   312.3     .06       0
  316.25      .1       0
Bank Sta=299.1,312.3
XS Rating Curve= 0 ,0
Exp/Cntr(USF)=0,0
Exp/Cntr=0.3,0.1

Type RM Length L Ch R = 1 ,1721    ,165.4,170.8,176.2
BEGIN DESCRIPTION:
Structure 4 XS 4
END DESCRIPTION:
XS GIS Cut Line= 4
1620401.44580309390483.2436861361620537.35052054390479.388233159
1620773.49701539390594.0879592291620963.37807451390606.618181405
#Sta/Elev= 30
       0  724.43    26.7  717.46    58.7  707.43    94.7  703.28   118.7  696.25
   134.7  696.53   152.4  694.53   216.7  692.93   245.8  689.31   276.9  688.55
   312.5  689.09     340  687.78   351.4  686.62   356.9  684.61   361.4  684.09
   381.6  684.56   383.6  684.93   388.1  688.74   394.9  698.46   405.1  707.51
   413.1  712.27   435.7  721.91   448.4  729.56   461.2  742.29   477.3  755.16
   497.3  775.99   513.4  789.43   557.4  820.21   570.3  828.49   588.8  838.73
#Mann= 8 ,-1,0
       0      .1       0      10     .05       0     110     .06       0
  325.96     .08       0  335.96     .06       0   356.9    .045       0
   381.6     .06       0  428.49      .1       0
#XS Ineff= 2 , 0
          291.52  707.27
Permanent Ineff=
       F       F
Bank Sta=356.9,381.6
XS Rating Curve= 0 ,0
Exp/Cntr(USF)=0,0
Exp/Cntr=0.3,0.1

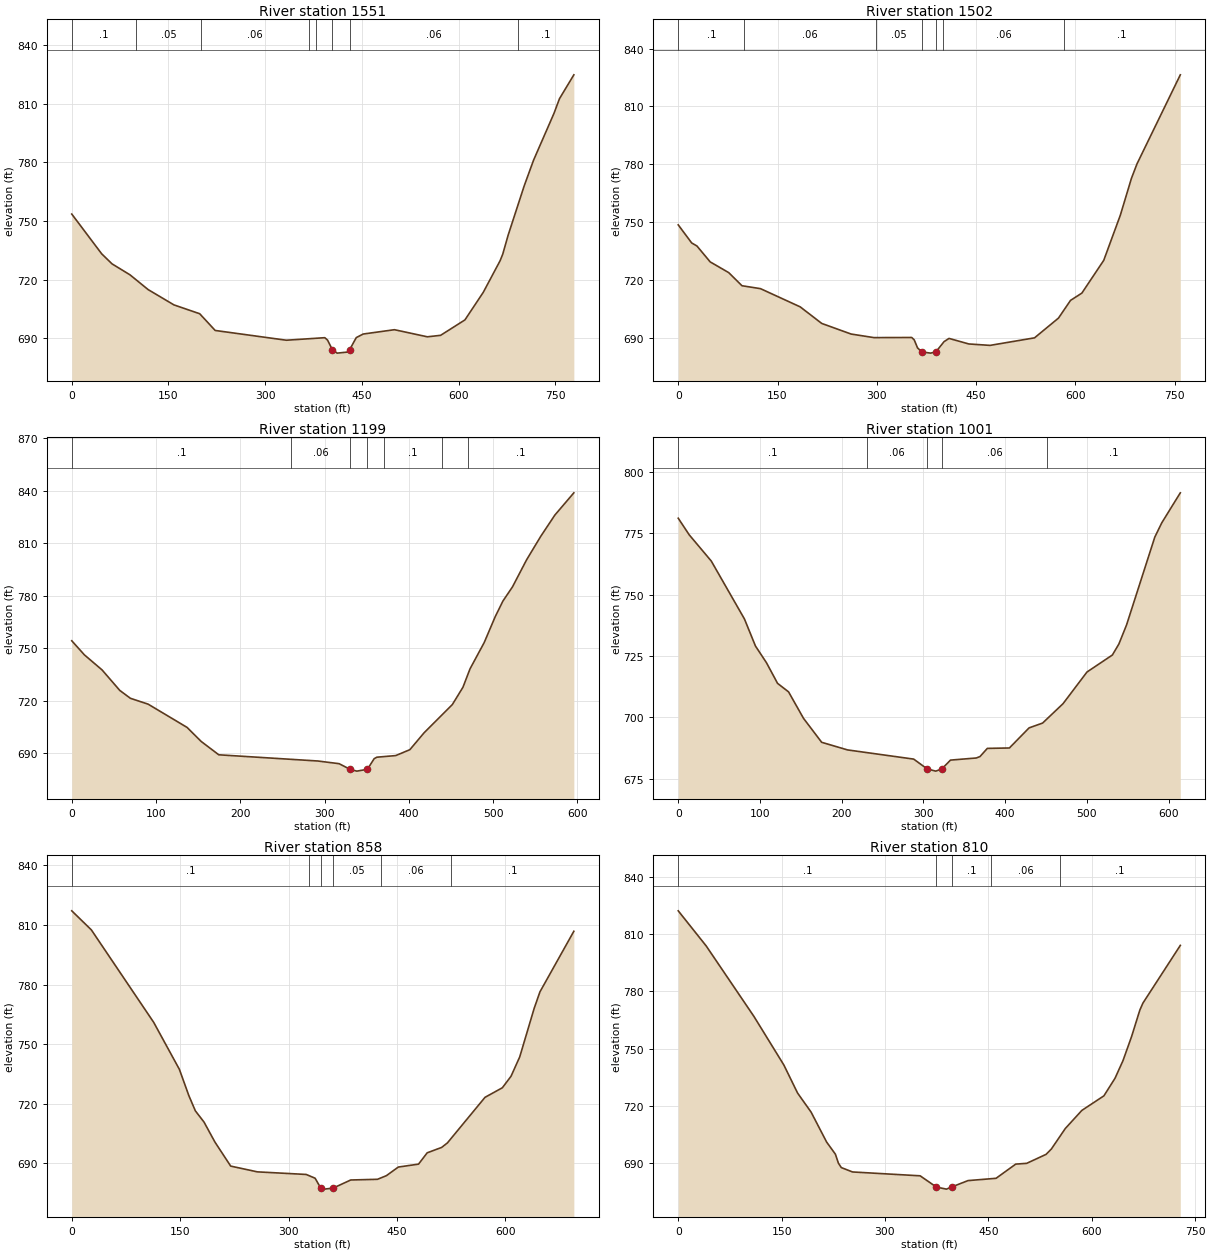
Type RM Length L Ch R = 1 ,1551    ,49,48.7,49.1
BEGIN DESCRIPTION:
Structure 4 XS 3
END DESCRIPTION:
XS GIS Cut Line= 6
1620313.73424786390549.7502499921620572.04959733390548.786386748
1620608.67640061390669.2692922841620658.79728932 390742.52289885
1620664.58046878390819.6319583931620881.44969875390887.102385493
#Sta/Elev= 30
       0  753.56    46.4  733.19    62.4  728.06    90.4   722.4   118.4  714.87
   158.4  707.03   198.4  702.49   222.4  693.92   332.8  688.92   392.4  690.22
   396.7  688.96   404.2  684.02   411.6  682.31   427.1  682.83  430.87  684.05
   441.2  690.27   451.9  692.09   500.4  694.31   551.5  690.67     572  691.43
   609.7  699.33   638.1  713.44   664.1  729.56   668.3  732.96   676.7  742.73
   701.4   767.8   716.1  781.14   747.9  805.23   756.3  812.65   778.6   824.9
#Mann= 8 ,-1,0
       0      .1       0     100     .05       0     200     .06       0
  368.23     .07       0  378.23     .06       0   404.2    .045       0
  430.87     .06       0  691.51      .1       0
Bank Sta=404.2,430.87
XS Rating Curve= 0 ,0
Exp/Cntr(USF)=0,0
Exp/Cntr=0.8,0.6

Type RM Length L Ch R = 1 ,1502    ,307.1,302.5,294.2
BEGIN DESCRIPTION:
Structure 4 XS 2
END DESCRIPTION:
XS GIS Cut Line= 6
1620311.80652137390589.2686430081620528.67575134390587.340916519
 1620577.8327768390711.6792750321620612.53185359390758.908574003
1620620.24275954390841.8008130111620874.70265604390919.873735799
#Sta/Elev= 30
       0  748.54    20.3  739.16    28.3  737.56    48.3  729.32    76.3  723.75
    96.3  716.95   124.3  715.43   184.3  705.98   216.9  697.37   261.3  691.87
   295.8  690.02   352.8  690.09   356.6  688.87   361.6  684.71     368  682.61
   381.4  681.97  389.38  682.63   401.7  687.94   409.2  689.61   439.1  686.73
   471.2  685.99   538.4   689.9   574.6  700.15   592.8  709.34   609.9  713.11
     643  730.12   668.1  753.59   684.8  772.63   693.2  780.16   758.7  826.41
#Mann= 7 ,-1,0
       0      .1       0     100     .06       0  298.65     .05       0
     368    .045       0  389.38     .05       0  400.59     .06       0
  582.51      .1       0
Bank Sta=368,389.38
XS Rating Curve= 0 ,0
Exp/Cntr(USF)=0,0
Exp/Cntr=0.3,0.1

Type RM Length L Ch R = 1 ,1199    ,196,198.2,199.6
BEGIN DESCRIPTION:
Structure 4 XS 1
END DESCRIPTION:
XS GIS Cut Line= 2
1620257.83017969390923.7291887761620825.54563058391104.935478702
#Sta/Elev= 30
       0  754.19      15  746.13      36   737.5      57  725.79    69.6  721.28
    90.6  717.94   136.8  704.65   153.6   696.6   174.5  688.96   292.1  685.41
   317.3  683.88   330.3680.6538   338.3  679.62   350.9  680.67   358.9  686.74
   362.1  687.59   384.5  688.51   401.3   691.9   418.1  701.52   451.7  717.71
   464.3  727.62   472.7  738.15   489.5  753.16   502.5  767.89   511.7   776.9
   523.1  785.05   539.8  800.49   556.6  813.93   573.4  826.12   595.9  838.83
#Mann= 7 ,-1,0
       0      .1       0     260     .06       0   330.3    .045       0
   350.9     .06       0     370      .1       0     440     .06       0
     470      .1       0
Bank Sta=330.3,350.9
XS Rating Curve= 0 ,0
Exp/Cntr(USF)=0,0
Exp/Cntr=0.3,0.1

Type RM Length L Ch R = 1 ,1001    ,144.4,142.6,140.1
BEGIN DESCRIPTION:
Structure 3 XS 4
END DESCRIPTION:
XS GIS Cut Line= 6
1620204.18498459391053.8894501781620287.46270518391096.946450666
1620365.18827151391137.1330500841620587.26197433391251.951389998
1620664.64305317391292.8049828411620753.00934626 391329.16678676
#Sta/Elev= 30
       0  781.16    13.4   774.4    40.4  763.71      81  740.09    94.5  729.05
     108  722.22   121.5  713.84     135  710.36   153.3  699.56   175.5   689.8
   207.1   686.7   288.1  682.95   304.7  678.92   315.1  678.05   322.5  678.94
   333.1  682.54   364.7  683.41   369.2  683.99   378.2  687.32   405.2  687.49
   429.3  695.69   445.8  697.64   470.8  705.54   500.1  718.45   531.2   725.4
   539.1  729.84   548.5  737.62   583.1  773.47   591.7  779.33   614.3  791.51
#Mann= 5 ,-1,0
       0      .1       0  231.25     .06       0   304.7    .045       0
   322.5     .06       0  451.25      .1       0
Bank Sta=304.7,322.5
XS Rating Curve= 0 ,0
Exp/Cntr(USF)=0,0
Exp/Cntr=0.3,0.1

Type RM Length L Ch R = 1 ,858     ,48.1,48.2,49
BEGIN DESCRIPTION:
Structure 3 XS 3
END DESCRIPTION:
XS GIS Cut Line= 5
1620109.91219038391198.5258042431620316.17099163391297.688689458
1620382.27958177391317.5212665011620535.65151091391353.219905178
1620774.96460722391350.575561573
#Sta/Elev= 30
       0  817.16    27.1  807.56   113.4  760.95   148.9   737.3     162  724.07
     171  716.39     183  710.73     198  700.72   219.9  688.55   256.8  685.65
   324.4  684.34   336.7  682.44   344.5   677.5     349  676.95   361.4  677.44
     386  681.55     423   681.9   435.3  683.72   451.8  688.07   479.8  689.54
   491.8  695.25   511.8  697.96   519.8  700.25   571.8   723.2   595.8  728.02
   607.8  733.83   619.8  743.55   639.8  768.01   647.8  776.34   694.7  806.86
#Mann= 6 ,-1,0
       0      .1       0  327.88     .05       0   344.5    .045       0
   361.4     .05       0  427.88     .06       0  525.35      .1       0
Bank Sta=344.5,361.4
XS Rating Curve= 0 ,0
Exp/Cntr(USF)=0,0
Exp/Cntr=0.3,0.1

Type RM Length L Ch R = 1 ,810     ,158.3,155.1,154.4
BEGIN DESCRIPTION:
Structure 3 XS 2
END DESCRIPTION:
XS GIS Cut Line= 4
1620076.85789531391250.0905045551620289.72755557391347.931217967
 1620534.3293391391398.1737464761620778.93112263391390.240715659
#Sta/Elev= 30
       0   822.2    40.5  803.85   109.9  766.89   153.3  741.47   173.2  726.79
   192.9  716.76   215.4   701.1   228.1  694.78   232.5  690.04   236.7  687.75
     253  685.46   351.1  683.44  374.78677.5308   389.3  676.47  396.68677.5656
   420.5  680.93   461.3  682.14   489.8  689.56   505.8  689.98   533.8  694.66
   541.6   697.5   561.8  708.22   585.8  717.69   617.8  725.32   633.9  734.49
   645.5  743.74   657.9  756.28   669.9  770.15   674.4  773.86   728.7   804.1
#Mann= 5 ,-1,0
       0      .1       0  374.78    .045       0  396.68      .1       0
  454.28     .06       0  553.99      .1       0
Bank Sta=374.78,396.68
XS Rating Curve= 0 ,0
Exp/Cntr(USF)=0,0
Exp/Cntr=0.3,0.1

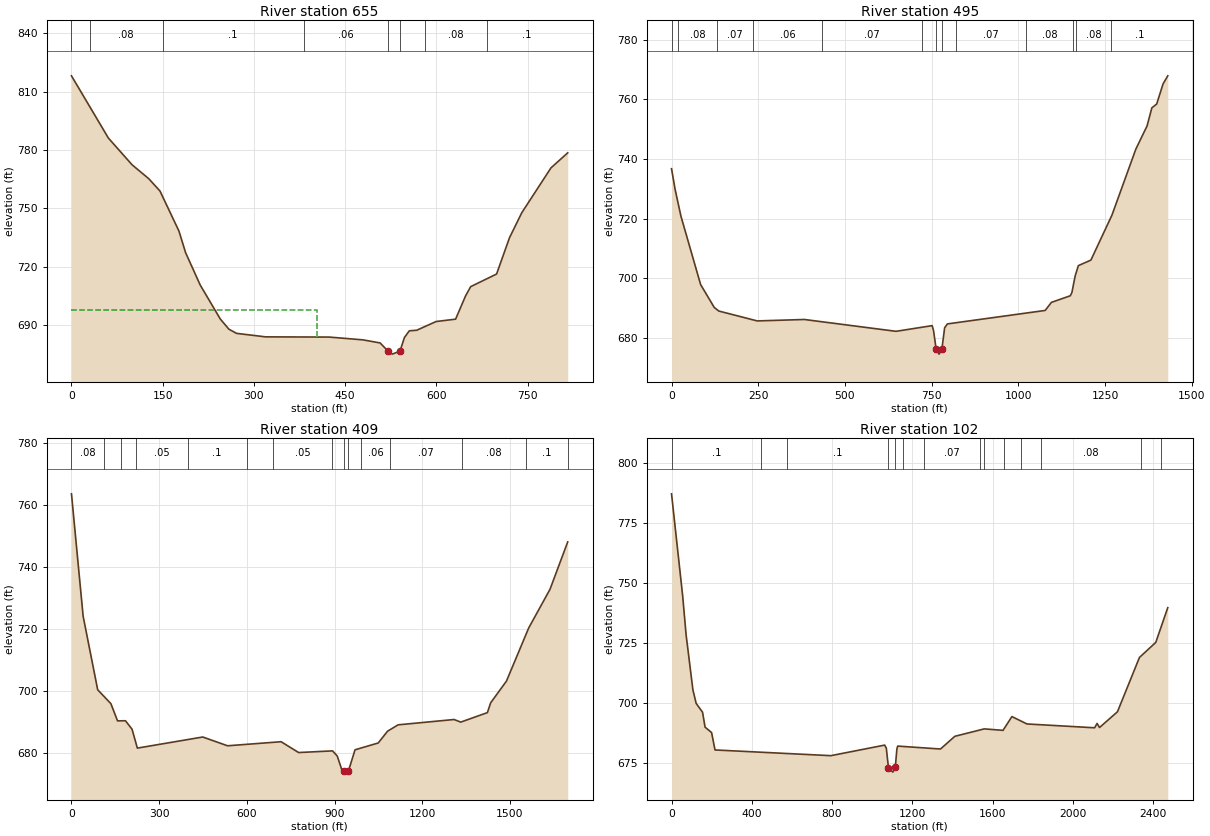
Type RM Length L Ch R = 1 ,655     ,159.5,159.9,159.7
BEGIN DESCRIPTION:
Structure 2 XS 4 AND Structure 3 XS 1
END DESCRIPTION:
XS GIS Cut Line= 4
1620010.74930517391332.0651563331620190.56467036391522.457895945
1620571.35014958391537.0017857771620733.97728134391477.504054648
#Sta/Elev= 30
       0  818.17    60.7  786.15    99.7  772.38   127.2  765.21   145.6  758.88
   176.7  738.32   187.7  727.17   211.7  710.53   244.6  693.11   258.8  687.82
   271.4  685.66   319.4  683.85   423.6  683.75   479.6   682.3   507.6  680.72
  520.66676.5266   527.6  674.97   540.2  676.52   547.6  683.53   555.6  686.97
   567.7  687.25   599.7  691.75   631.7  692.96     648  704.86   656.5  709.69
   699.1  716.18   720.4  734.89   740.6  747.76   788.6  770.82   816.1  778.54
#Mann= 8 ,-1,0
       0      .1       0      30     .08       0     150      .1       0
  381.88     .06       0  520.66    .045       0   540.2     .06       0
  581.88     .08       0  682.95      .1       0
#XS Ineff= 2 , 0
          402.96  697.63
Permanent Ineff=
       F       F
Bank Sta=520.66,540.2
XS Rating Curve= 0 ,0
Exp/Cntr(USF)=0,0
Exp/Cntr=0.3,0.1

Type RM Length L Ch R = 1 ,495     ,87,86.2,86.5
BEGIN DESCRIPTION:
Structure 2 XS 3
END DESCRIPTION:
XS GIS Cut Line= 6
1619771.43620885391531.7130985651619829.61176818391663.930278852
1620495.98635682391694.3402303181620605.72661646391708.884120149
1620749.84334297391720.7836663751620930.98087996 391404.78460549
#Sta/Elev= 30
       0  736.74    10.2  729.89    27.1  720.86    83.9  697.94   123.3  690.26
   136.4  689.07   247.1  685.76   383.2  686.24   647.5  682.28   751.6  684.18
   755.6  682.52  763.14676.3357   771.6  674.64   779.6  676.26   787.6  683.46
   795.6  684.76  1077.5  689.27  1095.5  691.97  1150.1  694.19  1154.7  695.31
  1163.9  700.75  1173.2  704.28  1209.4  706.13    1270  721.16  1339.1  743.33
  1371.4  751.07  1385.2  757.13  1399.1   758.4  1417.5  765.14  1431.1  767.85
#Mann= 13 ,-1,0
       0      .1       0      20     .08       0     130     .07       0
  234.45     .06       0  434.45     .07       0  723.54     .06       0
  763.14    .045       0   779.6     .06       0  821.53     .07       0
 1022.23     .08       0 1156.84     .07       0 1166.84     .08       0
 1266.84      .1       0
Bank Sta=763.14,779.6
XS Rating Curve= 0 ,0
Exp/Cntr(USF)=0,0
Exp/Cntr=0.3,0.1

Type RM Length L Ch R = 1 ,409     ,309.3,307.1,305.7
BEGIN DESCRIPTION:
Structure 1 XS 2
END DESCRIPTION:
XS GIS Cut Line= 6
1619640.14944576391553.2269558021619746.24965216391754.001192533
1620350.20467322391773.588922946 1620568.9343295391783.382788153
1620794.19322925391789.9120316231620996.59977685391419.377464648
#Sta/Elev= 30
       0  763.48    39.9  724.03    89.7  700.33   134.9  695.84   157.6   690.3
   184.7  690.34   207.3  687.61   225.4  681.52   449.1   685.1     534  682.27
   717.2  683.58   777.3  680.09   893.3  680.63   909.4  678.96   925.4  674.42
   933.4  674.02   941.4  673.78  947.35 674.063   970.2  680.98  1049.5  683.17
  1081.5  686.97  1117.5  689.02  1309.1  690.74  1331.9   689.9  1423.1  692.96
  1434.3  696.13  1488.3  703.12  1564.4  720.24  1637.3  732.71  1697.9  747.99
#Mann= 15 ,-1,0
       0     .08       0     110      .1       0     170     .07       0
     220     .05       0  397.08      .1       0  599.91     .07       0
  689.91     .05       0  891.37     .07       0   933.4    .045       0
  947.35     .07       0  991.37     .06       0 1090.32     .07       0
 1335.67     .08       0 1555.67      .1       0 1697.88     .06       0
Bank Sta=933.4,947.35
XS Rating Curve= 0 ,0
Exp/Cntr(USF)=0,0
Exp/Cntr=0.3,0.1

Type RM Length L Ch R = 1 ,102     ,,,
BEGIN DESCRIPTION:
Structure 1 XS 1
END DESCRIPTION:
XS GIS Cut Line= 6
1619483.44760246 391576.079307951619581.38625452391855.204466333
1620092.29955612392016.8032422391620492.21571872 392080.46336608
1620947.63045081392170.2404638061621081.47994197391409.583599441
#Sta/Elev= 30
       0  787.24    55.6  744.69    72.5  728.66   106.5  705.67   122.8  699.99
   154.6  696.34   167.2  690.11   199.7  687.86   216.7  680.62     794  678.24
  1062.4  682.64  1070.5  681.35 1081.28673.1741  1102.9  671.39  1115.1  673.34
  1123.2  681.02  1127.2  682.23  1340.5  681.01  1411.9   686.3  1558.7  689.39
  1652.2  688.78  1696.4  694.51  1771.4  691.44  2108.7  689.85  2120.9  691.66
  2133.1  689.96  2222.5  696.52  2332.1  719.13  2413.4  725.39  2473.2  739.85
#Mann= 14 ,-1,0
       0      .1       0  445.81     .05       0  575.81      .1       0
 1081.28    .045       0  1115.1      .1       0 1151.74     .06       0
 1256.69     .07       0 1536.69     .05       0 1556.69     .07       0
 1656.69      .1       0 1740.87     .07       0 1840.87     .08       0
 2340.87     .07       0 2440.87     .06       0
Bank Sta=1081.28,1115.1
XS Rating Curve= 0 ,0
Exp/Cntr(USF)=0,0
Exp/Cntr=0.3,0.1
LCMann Table=0

Chan Stop Cuts=-1
Use User Specified Reach Order=0
Composite Channel Slope=5